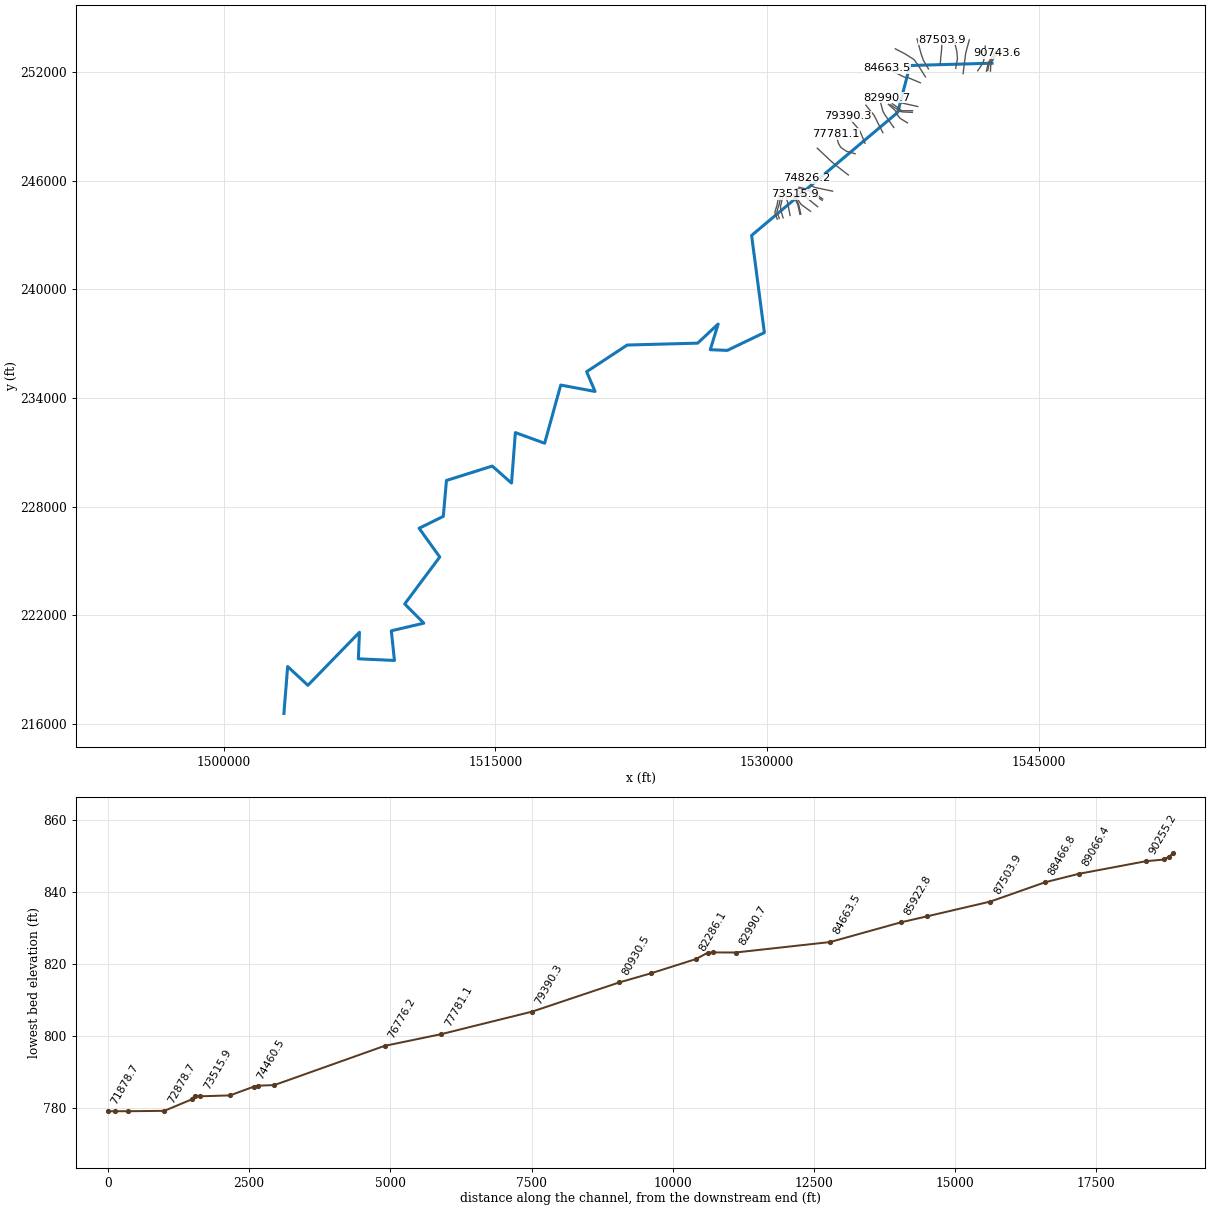
--- INDNCR.prj (project) ---

Proj Title=INDNCR
Current Plan=p01
Default Exp/Contr=0,0
English Units
Geom File=g01
Flow File=f01
Plan File=p01
BEGIN DESCRIPTION:
END DESCRIPTION:
DSS Export Rating Curves= 0
DSS Export Rating Curve Sorted= 0
DSS Export Volume Flow Curves= 0
DXF OffsetX= 0
DXF OffsetY= 0
DXF ScaleX= 0
DXF ScaleY= 0

--- INDNCR.p01 (plan) ---

Plan Title=Floodplain
Program Version=4.00
Geom File=g01
Flow File=f01
K Sum by GR=0
Std Step Tol=0.01
Critical Tol=0.01
Num of Std Step Trials=20
Max Error Tol=0.3
Flow Tol Ratio=0.001
Split Flow NTrial=30
Split Flow Tol=0.02
Split Flow Ratio=0.02
Log Output Level=0
Friction Slope Method=1
Unsteady Friction Slope Method=2
Unsteady Bridges Friction Slope Method=1
Global Log Level=0
CheckData=False
Run HTab=0
Run UNet=0
Run PostProcess=0
UNET Theta=0
UNET Theta Warmup=0
UNET ZTol=0
UNET ZSATol=0
UNET MxIter=0
UNET MaxInSteps=0
UNET DtIC=0
UNET DtMin=0
UNET MaxCRTS=0
UNET WFStab=0
UNET SFStab=0
UNET WFX=0
UNET SFX=0
UNET DSS MLevel=0
UNET DZMax Abort=0
UNET Convert EG Bridges=0
UNET Use Existing IB Tables=0
UNET Froude Limit=0
UNET Froude Power=0
Write IC File=0
Echo Input=False
Echo Output=False
Write Detailed=0

--- INDNCR.f01 (steady flow) ---

Flow Title=NFF Regression Equation
Program Version=4.10
Number of Profiles= 1
Profile Names=P100yr
River Rch & RM=INDNCR,Main            ,90743.6
812.7351
River Rch & RM=INDNCR,Main            ,90255.2
1057.248
River Rch & RM=INDNCR,Main            ,89066.4
1082.549
River Rch & RM=INDNCR,Main            ,88466.8
  1162.4
River Rch & RM=INDNCR,Main            ,86376.5
1210.457
River Rch & RM=INDNCR,Main            ,85922.8
1281.791
River Rch & RM=INDNCR,Main            ,82590.7
 1343.59
River Rch & RM=INDNCR,Main            ,82286.1
1464.304
River Rch & RM=INDNCR,Main            ,80930.5
 1547.28
River Rch & RM=INDNCR,Main            ,79390.3
 1618.18
River Rch & RM=INDNCR,Main            ,76776.2
1697.579
River Rch & RM=INDNCR,Main            ,72228.9
1820.874
River Rch & RM=INDNCR,Main            ,71450.2
2072.238
River Rch & RM=INDNCR,Main            ,70253.5
2084.725
River Rch & RM=INDNCR,Main            ,69345.6
 2271.58
River Rch & RM=INDNCR,Main            ,63780.4
2395.041
River Rch & RM=INDNCR,Main            ,63438.9
3431.876
River Rch & RM=INDNCR,Main            ,60197
3531.823
River Rch & RM=INDNCR,Main            ,51255.1
3737.896
River Rch & RM=INDNCR,Main            ,50788
4194.356
River Rch & RM=INDNCR,Main            ,43039.8
4310.634
River Rch & RM=INDNCR,Main            ,42512.9
4680.594
River Rch & RM=INDNCR,Main            ,30264.8
4989.112
River Rch & RM=INDNCR,Main            ,21884.3
5259.439
River Rch & RM=INDNCR,Main            ,21259.3
5563.439
River Rch & RM=INDNCR,Main            ,19044.6
5597.618
River Rch & RM=INDNCR,Main            ,17897.7
5677.075
River Rch & RM=INDNCR,Main            ,427.5
6025.102
River Rch & RM=INDNCR,Main            ,222.3
6025.803
Boundary for River Rch & Prof#=INDNCR,Main            , 1
Up Type= 0
Dn Type= 3
Dn Slope=0.00042
DSS Import GetInterval= 0
DSS Import GetPeak= 0
DSS Import FillOption= 0

--- INDNCR.g01 (geometry) ---

Geom Title=USGS 10m DEM
Program Version=4.10

River Reach=INDNCR          ,Main
Reach XY= 30
     1542429.183      252476.749     1537898.785      252348.924
     1537221.143      249761.965      1529154.41      242967.479
     1529857.898       237603.21     1527811.388      236620.745
     1526872.152      236659.807     1527307.048      238076.474
     1526176.102      237020.561     1522286.202      236916.776
     1520046.939       235444.53     1520510.373      234354.925
     1518615.581      234705.967     1517727.028      231493.999
     1516111.881       232080.92     1515899.782      229293.952
     1514835.893       230234.23     1512306.877      229438.789
     1512132.919       227458.58     1510798.544      226798.685
     1511937.086      225213.789     1510002.723      222622.762
      1511057.63      221561.586     1509263.185      221139.364
     1509435.408      219503.208     1507444.653       219593.14
     1507503.022      221057.637     1504656.749      218130.166
     1503539.871      219168.165     1503333.076      216580.761

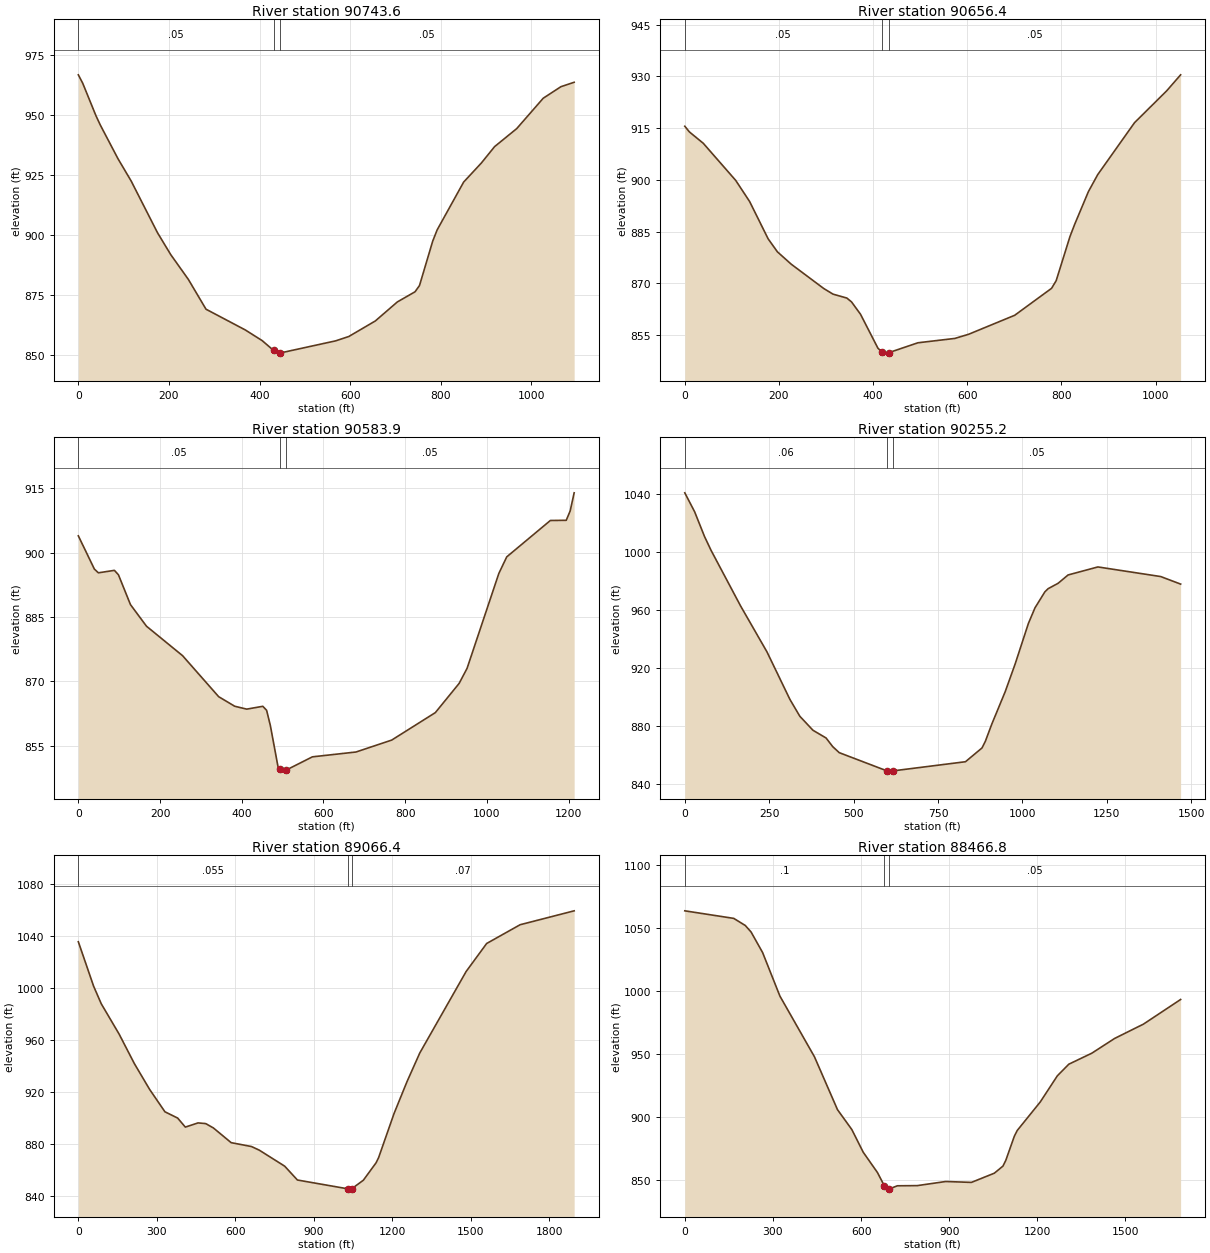
Type RM Length L Ch R = 1 ,90743.6 ,93.1,87.2,81.6
XS GIS Cut Line= 4
     1542341.509      252040.551      1542358.87      252389.943
     1542393.593      252535.343      1542725.58      253029.266
#Sta/Elev= 30
       0  966.55     9.7  963.05    38.9  949.53    48.6  945.62    87.5  931.64
   116.6  922.36   174.9  900.78   204.1  891.69   242.9   881.4   281.8  869.01
   368.5  860.38   405.9  855.92   430.8  851.88   443.2  850.73   445.8   850.8
   567.6  855.82   596.9  857.64   655.4   864.1   704.2  872.04   743.2  876.26
     753  878.85   782.2  897.33     792  902.01   850.5  921.92   889.6  929.86
   918.8  936.67   967.6  944.16  1026.2  956.82  1065.2  961.61  1094.4  963.45
#Mann= 3 , 0 , 0
       0     .05       0   430.8    .045       0   445.8     .05       0
Bank Sta=430.8,445.8
XS Rating Curve= 0 ,0
Exp/Cntr=0.3,0.1

Type RM Length L Ch R = 1 ,90656.4 ,71,72.6,75.3
XS GIS Cut Line= 4
     1542189.599      252073.103     1542265.554      252429.006
     1542311.127      252520.152     1542628.792      253014.075
#Sta/Elev= 30
       0  915.56     9.8  913.91    39.3  910.61   108.2  899.85   137.7  893.74
     177  882.93   196.7  879.16   226.2  875.56   295.1  868.53   314.7   866.9
   344.2  865.76   354.1  864.65   373.2  861.07   410.2  851.23   418.1  850.22
   428.8   849.8   433.1  849.93   495.2   852.8   573.5  854.06   602.8  855.26
   700.7  860.77     779  868.58   788.8   870.8   818.2  883.64     828   887.1
   857.3  896.63   876.9  901.51   955.2  916.59  1023.7  925.85  1053.1  930.46
#Mann= 3 , 0 , 0
       0     .05       0   418.1    .045       0   433.1     .05       0
Bank Sta=418.1,433.1
XS Rating Curve= 0 ,0
Exp/Cntr=0.3,0.1

Type RM Length L Ch R = 1 ,90583.9 ,326.5,328.7,329.6
XS GIS Cut Line= 4
     1542118.324       252037.71     1542216.075      252478.485
     1542261.648      252569.631     1542623.584      253121.714
#Sta/Elev= 30
       0  903.92    39.3  896.16    49.1  895.29    88.3  895.87    98.2  894.83
   127.6  887.88   166.8  882.84   255.2  875.96   343.5   866.4   382.8  864.17
   412.2   863.5   451.5  864.16   460.8  863.23     470  859.67   488.5  850.17
     494   849.5   497.8  849.04     509   849.3   572.8  852.37   679.6   853.5
     767  856.28   873.8  862.69     932   869.5   951.4  873.01  1029.1  895.13
  1048.5  899.01  1155.3   907.5  1194.1  907.54  1203.8  909.74  1213.5  913.95
#Mann= 3 , 0 , 0
       0     .05       0     494    .045       0     509     .05       0
Bank Sta=494,509
XS Rating Curve= 0 ,0
Exp/Cntr=0.3,0.1

Type RM Length L Ch R = 1 ,90255.2 ,1181.3,1188.7,1191.1
XS GIS Cut Line= 4
     1541635.685      252056.807     1541920.407       252475.21
     1541977.699      252664.446     1542057.221        253425.1
#Sta/Elev= 30
       0 1041.11    29.2 1027.98    58.4 1010.88    77.9 1001.27   165.4  962.78
   243.3   931.1   311.4  898.17   340.6  886.56   379.6  876.84   418.5  871.48
     438  865.54   457.4  861.34   600.3   848.6   609.7  848.56   615.3  848.69
   831.3  855.06   880.3  864.59   890.1  869.13   909.7  881.32   948.9  903.46
   978.4  922.64  1017.6  950.66  1037.2  961.53  1066.6  972.61  1076.4  974.83
  1105.8  978.52  1135.2  984.27  1223.5  989.83  1409.8  983.17  1468.6  977.96
#Mann= 3 , 0 , 0
       0     .06       0   600.3    .045       0   615.3     .05       0
Bank Sta=600.3,615.3
XS Rating Curve= 0 ,0
Exp/Cntr=0.3,0.1

Type RM Length L Ch R = 1 ,89066.4 ,589.9,599.6,603.7
XS GIS Cut Line= 4
      1540830.13      251900.557     1540945.969      252818.744
     1540975.963      253039.446     1541170.407      253761.669
#Sta/Elev= 30
       0 1035.81    58.4 1001.57    87.7  987.98   155.9  964.64   214.3  941.83
   272.8   921.9   331.2  904.69   379.9  899.84   409.2  892.88   457.9  896.12
   487.1  895.58   516.3  892.26   584.5  880.88   662.4  877.88   691.7  875.13
   789.1  862.76   837.8  852.08  1030.9  845.27  1041.7  845.05  1045.9  845.39
  1090.1  851.94  1138.5  865.32  1148.2  869.28  1207.2  903.28  1256.4   927.7
  1305.7  950.01  1482.8  1012.8  1561.5 1034.47  1689.5 1048.94  1896.1 1059.66
#Mann= 3 , 0 , 0
       0    .055       0  1030.9    .045       0  1045.9     .07       0
Bank Sta=1030.9,1045.9
XS Rating Curve= 0 ,0
Exp/Cntr=0.3,0.1

Type RM Length L Ch R = 1 ,88466.8 ,965.1,962.9,957.4
XS GIS Cut Line= 4
      1540423.88      252193.092      1540517.63      252724.342
      1540486.38      253120.175     1540305.824      253849.342
#Sta/Elev= 30
       0 1063.53   166.7 1057.53     206 1051.87   225.6 1046.74   264.8 1030.45
   323.7   995.9   441.4  947.68   519.8  905.72   568.5  889.99   607.2  872.02
   655.7  855.88   679.5  845.23   694.4  842.69   694.5   842.7   723.5  845.34
   791.3  845.47   888.1  848.74   975.6  848.03  1053.6  855.33  1082.9  860.95
  1092.6  865.51  1121.9  884.79  1131.6  889.25  1209.7  911.79  1268.2  932.63
  1307.2  941.83  1385.3  950.54  1463.3  962.29  1560.9  973.58  1687.7  993.17
#Mann= 3 , 0 , 0
       0      .1       0   679.5    .045       0   694.5     .05       0
Bank Sta=679.5,694.5
XS Rating Curve= 0 ,0
Exp/Cntr=0.3,0.1

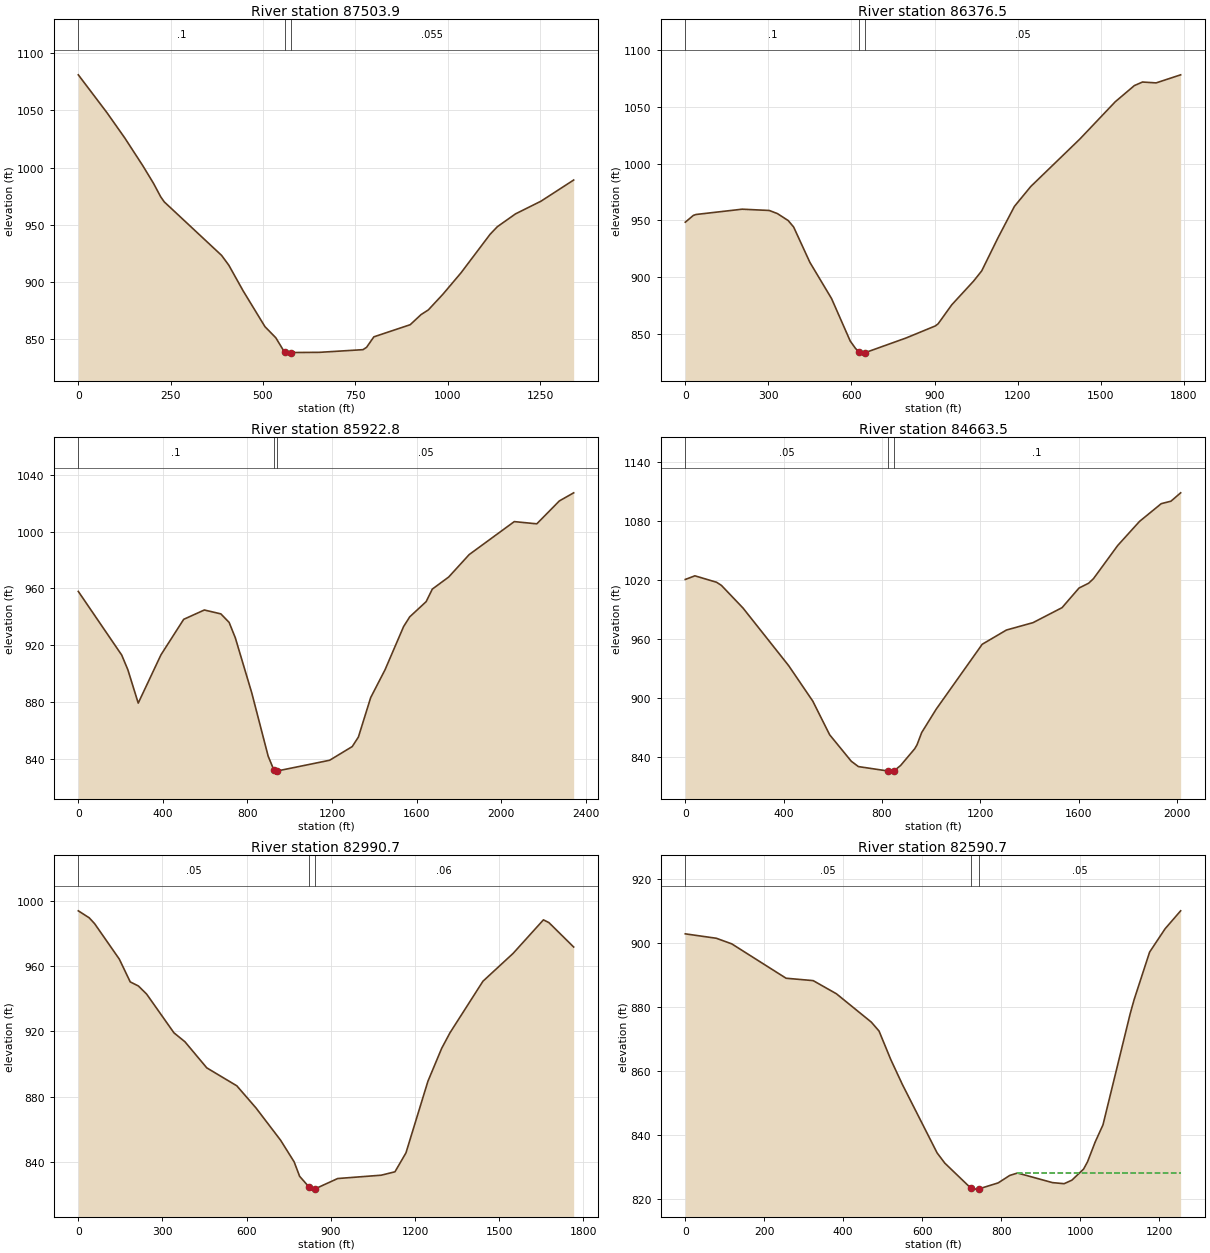
Type RM Length L Ch R = 1 ,87503.9 ,1115.1,1127.4,1137
XS GIS Cut Line= 4
     1539569.591      252429.874     1539604.313      252855.221
     1539639.035      253167.721     1539673.757       253766.68
#Sta/Elev= 30
       0 1081.25    77.6 1048.07   126.1 1025.79   174.6 1001.63   203.7  986.12
   223.1  974.34   232.8  969.88     388  922.99   407.4  914.47   446.4  891.88
   505.4  860.54   534.8   850.8   554.5  840.26   560.1   838.6   564.3  837.36
   575.1  837.88   652.8  838.05   770.7  840.39   780.5  842.44   800.2  851.62
   898.6  862.27   928.1  871.15   947.7  875.23   987.1  888.95  1036.2  907.74
  1114.9  941.49  1134.6  948.16  1183.8  959.41  1252.6  970.49  1341.2  989.06
#Mann= 3 , 0 , 0
       0      .1       0   560.1    .045       0   575.1    .055       0
Bank Sta=560.1,575.1
XS Rating Curve= 0 ,0
Exp/Cntr=0.3,0.1

Type RM Length L Ch R = 1 ,86376.5 ,446.9,453.7,459.1
XS GIS Cut Line= 4
     1538920.285      252160.777      1538644.71       252622.69
     1538523.272      252956.547     1538288.514      253820.499
#Sta/Elev= 30
       0  948.43    29.3  954.44    39.1  955.22   205.4  959.87   303.2  958.74
   332.5  956.02   371.6  949.86   391.2  944.19   449.9  913.07   528.1  881.23
   595.5  843.85   614.7  837.32   628.2  834.09   643.2  833.23  647.23833.4553
   797.1  846.55     903  857.18   912.8  859.01     962  875.73  1040.7  896.56
  1070.2   905.6  1129.2  934.82  1188.3  962.33  1247.3  979.84  1424.4 1021.56
  1552.3 1054.39  1621.2 1068.61  1650.7 1071.76  1699.9 1070.99  1788.4 1078.09
#Mann= 3 , 0 , 0
       0      .1       0   628.2    .045       0  647.23     .05       0
Bank Sta=628.2,647.23
XS Rating Curve= 0 ,0
Exp/Cntr=0.3,0.1

Type RM Length L Ch R = 1 ,85922.8 ,1194.6,1259.3,1277
XS GIS Cut Line= 5
     1538754.175        251718.7     1538337.508      252380.158
     1538129.175      252671.825     1537629.175      252989.533
     1537087.508      253270.783
#Sta/Elev= 30
       0   957.9   205.2   913.2   234.5  902.81   283.4  879.41   390.9  913.33
   498.4  938.28   596.1  944.84   674.3  942.11   713.4   936.1   742.7  925.25
   820.5  886.53     898  842.11   925.6  832.16   936.8   831.6   940.6   831.7
  1188.7  839.24  1295.6  848.86  1324.7  855.54    1383  883.33    1451  902.91
  1538.4  933.16  1567.5  940.02  1645.2  950.72  1674.3  959.52    1752  968.04
  1848.8   983.8    2062 1006.96  2168.5  1005.4  2275.1 1021.48  2342.9 1027.19
#Mann= 3 , 0 , 0
       0      .1       0   925.6    .045       0   940.6     .05       0
Bank Sta=925.6,940.6
XS Rating Curve= 0 ,0
Exp/Cntr=0.3,0.1

Type RM Length L Ch R = 1 ,84663.5 ,1643.1,1672.8,1661.1
XS GIS Cut Line= 4
     1538468.896      251396.888     1537836.952      251660.777
     1537566.119      251716.332     1536628.619      252195.499
#Sta/Elev= 30
       0    1021    39.1 1024.69   127.2 1018.14   146.8 1014.99   234.8  991.91
   420.7  933.23   518.5  897.26     587  863.07     675  836.14   703.9  830.72
  826.18 826.146   827.8   826.1  847.62 826.178   875.5  831.83   932.7  848.78
   942.2  852.81   961.3  865.35  1020.3  889.12  1207.3  955.08  1305.7  969.55
  1413.9  977.07    1532  992.32  1600.9 1012.26  1640.2  1017.2  1659.9 1021.84
  1758.3 1055.53  1846.9 1079.99  1935.4 1098.08  1974.8 1100.57  2014.2 1109.08
#Mann= 3 , 0 , 0
       0     .05       0  826.18    .045       0  847.62      .1       0
Bank Sta=826.18,847.62
XS Rating Curve= 0 ,0
Exp/Cntr=0.3,0.1

Type RM Length L Ch R = 1 ,82990.7 ,415,400,384.3
XS GIS Cut Line= 4
     1538326.535      250086.124     1537632.091      250238.902
     1537291.813      250315.291     1536632.091      250565.291
#Sta/Elev= 30
       0  993.89      39  989.59    58.4  985.96   146.1  964.28   185.1  950.29
   214.3  947.78   243.5  942.82   340.9  919.06   379.9   913.6   457.8  897.58
   564.9  886.56   633.1  873.02   720.7  853.24   769.2  839.92   788.6  831.09
   823.3   824.3     837   823.2  842.35823.2534   924.2  829.69  1079.4  831.74
  1128.4  833.82  1167.6  845.42    1246   889.4    1295  909.58  1324.4  919.06
    1442  950.71  1549.7  967.82  1657.5  988.35  1677.1  986.67  1765.3   971.7
#Mann= 3 , 0 , 0
       0     .05       0   823.3    .045       0  842.35     .06       0
Bank Sta=823.3,842.35
XS Rating Curve= 0 ,0
Exp/Cntr=0.3,0.1

Type RM Length L Ch R = 1 ,82590.7 ,92.7,87.6,82.3
XS GIS Cut Line= 5
     1538044.446        249855.8     1537514.498      249850.592
     1537380.384      249879.237     1537304.139      249978.485
     1536922.195      250238.902
#Sta/Elev= 30
       0  902.91    78.5  901.54   117.8  899.78   255.2  889.06   323.9  888.31
   382.8   884.2   471.1  875.36   490.7  872.57   520.2  863.73   549.6  855.94
   637.7  834.54   657.3  831.33   722.5823.6154   734.5  823.22   744.1  823.32
   792.3  825.16   821.8   827.5   841.4  828.25     930  825.25   959.5  824.92
   979.1  826.02  1008.6  829.47  1018.5   831.7  1038.2  837.97  1057.8  843.28
  1126.7  877.97  1136.5  882.31  1175.9  897.22  1215.2  904.51  1254.5   910.1
#Mann= 3 , 0 , 0
       0     .05       0   722.5    .045       0   744.1     .05       0
#XS Ineff= 2 , 0
                          840.34          828.33
Permanent Ineff=
       F       F
Bank Sta=722.5,744.1
XS Rating Curve= 0 ,0
Exp/Cntr=0.3,0.1

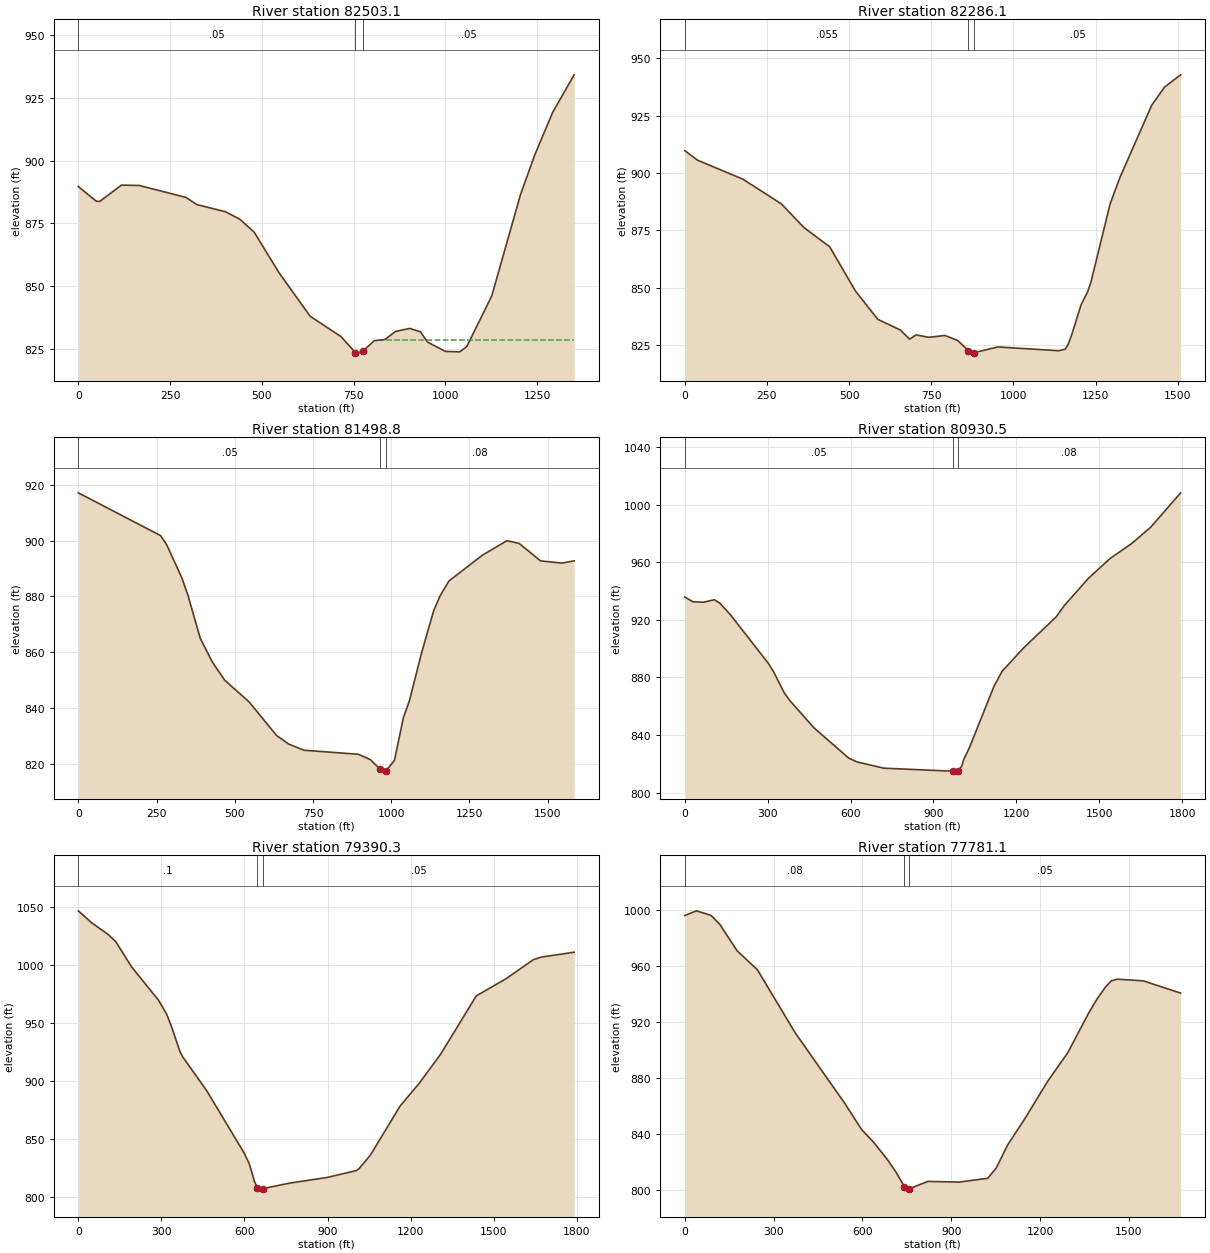
Type RM Length L Ch R = 1 ,82503.1 ,223.2,217,211
XS GIS Cut Line= 6
     1538026.651      249762.918     1537479.776      249786.789
     1537306.165      249825.852     1537264.932      249906.147
     1537050.088      250018.994     1536811.373      250188.265
#Sta/Elev= 30
       0  889.64    48.9  883.77    58.6  883.71   117.3  890.19   166.2  890.05
   293.2  885.29   322.6  882.44   400.8  879.58   439.9  876.61     479  871.45
   547.4  855.11   631.7  837.87     716  829.73  754.82823.3851   761.4  823.16
  776.44824.1414   806.6  828.16     835  828.55   864.2  831.81     903  833.02
   932.1  831.67   951.5  827.55    1000  823.85  1038.9  823.66  1058.3  825.75
  1126.6  846.06  1204.6  886.38  1243.6  902.26  1292.4  919.22  1350.9   934.2
#Mann= 3 , 0 , 0
       0     .05       0  754.82    .045       0  776.44     .05       0
#XS Ineff= 2 , 0
                          815.26          828.54
Permanent Ineff=
       F       F
Bank Sta=754.82,776.44
XS Rating Curve= 0 ,0
Exp/Cntr=0.3,0.1

Type RM Length L Ch R = 1 ,82286.1 ,774.6,787.3,792.9
XS GIS Cut Line= 5
     1537760.592      249182.478     1537359.116      249427.704
     1537133.422      249707.652     1537116.061       249829.18
     1536705.904      250204.614
#Sta/Elev= 30
       0  909.74    39.2  905.54   176.4  897.32     294  886.49   362.6  876.16
     441  867.76     519  848.54   587.1  836.12   655.1  831.52   684.3  827.46
   703.7  829.32   742.6  828.26   791.2  829.08     830  826.92   863.3  822.48
   877.3  821.36  880.59821.5826   952.8  824.06  1138.2  822.41  1157.7  823.11
  1167.4  825.46  1177.2  829.31  1206.4  842.65  1225.9  848.18  1235.7  852.23
  1294.2  886.46  1323.5  897.83    1421  929.63  1460.1   937.5  1508.8  942.83
#Mann= 3 , 0 , 0
       0    .055       0   863.3    .045       0  880.59     .05       0
Bank Sta=863.3,880.59
XS Rating Curve= 0 ,0
Exp/Cntr=0.3,0.1

Type RM Length L Ch R = 1 ,81498.8 ,572.3,568.3,566.5
XS GIS Cut Line= 4
     1537003.394      248927.848     1536521.624      249613.612
     1536404.436      249821.946     1536274.228      250312.397
#Sta/Elev= 30
       0  917.07   263.1  901.74   282.6  898.45   331.3  886.52   350.8  880.19
   389.8  864.94   428.8  856.41   467.8  849.99   545.7  842.24   633.4  830.22
   672.4  827.12   721.1  824.92   895.4  823.47   933.7  821.52   965.3  818.03
   981.5  817.44   983.3817.5413  1010.2  821.26  1038.9   836.6    1058  842.59
  1096.6   859.6  1135.7  874.89  1155.2  879.96  1184.4  885.51  1291.8  894.78
  1369.9  899.92  1408.9  898.95  1477.2  892.71  1545.5  891.91  1584.6  892.72
#Mann= 3 , 0 , 0
       0     .05       0   965.3    .045       0   983.3     .08       0
Bank Sta=965.3,983.3
XS Rating Curve= 0 ,0
Exp/Cntr=0.3,0.1

Type RM Length L Ch R = 1 ,80930.5 ,1538.1,1540.2,1551.7
XS GIS Cut Line= 4
     1536400.096       248641.39     1536061.554      249309.793
     1535922.665      249587.571     1535462.596      250160.487
#Sta/Elev= 30
       0  935.79    29.2  932.46    68.1  932.15     107  933.88   126.5  931.59
   165.4  923.39   301.6  889.91   321.1  883.99     360  869.26   379.5  864.03
   467.1  845.03   593.6  823.89   622.8   821.3   720.1  816.93   962.8  814.88
   972.5  814.94   988.8  815.26  1001.6  818.11  1011.3  823.71  1030.7  831.41
  1118.6  873.57    1148  884.07  1226.4  900.48  1343.9   921.9  1373.3  929.74
  1461.5   948.9  1539.9   962.6  1618.2  973.01  1686.8  984.33  1794.6 1008.11
#Mann= 3 , 0 , 0
       0     .05       0   972.5    .045       0   988.8     .08       0
Bank Sta=972.5,988.8
XS Rating Curve= 0 ,0
Exp/Cntr=0.3,0.1

Type RM Length L Ch R = 1 ,79390.3 ,1596,1609.2,1616.9
XS GIS Cut Line= 4
     1535414.853      248059.793      1535223.88      248524.203
     1535089.332      248810.661     1534451.311      249544.168
#Sta/Elev= 30
       0 1046.46    48.3 1036.12   106.2  1026.4   135.2  1019.9   193.1  997.98
   289.7  969.45   318.7  957.63     338  945.86     367   925.3   376.6  920.84
   463.5  891.61     598   838.2   617.2   828.8   636.4  813.26     646  808.16
   655.6  806.78   665.2  807.12   761.1  811.88   897.2  816.76  1005.2  822.82
    1015  824.74  1054.3  835.87  1162.3  878.37  1231.1   897.9  1309.6  923.33
  1437.3  973.22  1545.3  988.04  1643.5 1004.39    1673 1006.65  1790.8 1010.83
#Mann= 3 , 0 , 0
       0      .1       0     646    .045       0   665.2     .05       0
Bank Sta=646,665.2
XS Rating Curve= 0 ,0
Exp/Cntr=0.3,0.1

Type RM Length L Ch R = 1 ,77781.1 ,1008.5,1004.9,1001.2
XS GIS Cut Line= 5
     1534872.318      247478.196     1534390.315      247614.302
     1534077.815      247827.843     1533947.606      248051.802
     1533800.269      248567.605
#Sta/Elev= 30
       0  995.86    39.3  999.21    88.4  995.98   117.8  989.73   176.8  970.69
   245.5  957.06   373.2  912.04   539.7  861.96   597.9  842.88   636.7  834.28
   685.2   821.4   714.4  812.33   741.4  802.38   753.2  800.52   756.4  800.66
   821.1  806.02   927.3  805.55  1023.3  808.27    1052  815.62  1090.4  832.04
  1148.2  850.64  1226.2  877.66  1294.5   898.2  1362.7  925.64    1392  936.09
  1421.2  944.88  1440.8  949.23  1460.3  950.42    1548  949.24  1674.8  940.48
#Mann= 3 , 0 , 0
       0     .08       0   741.4    .045       0   756.4     .05       0
Bank Sta=741.4,756.4
XS Rating Curve= 0 ,0
Exp/Cntr=0.3,0.1

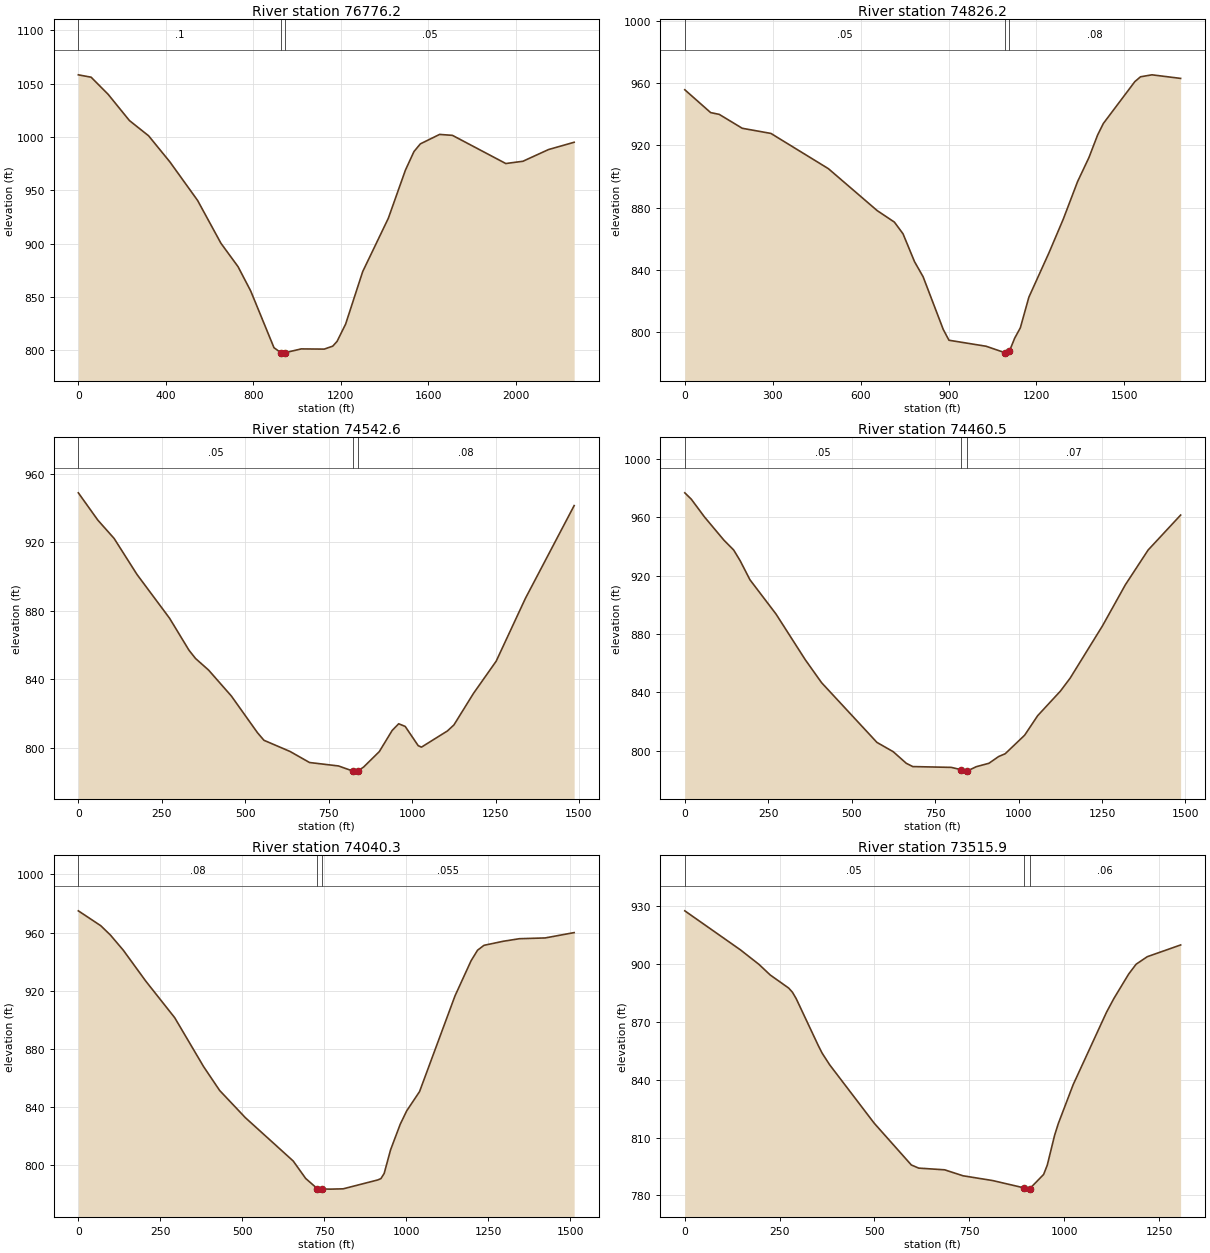
Type RM Length L Ch R = 1 ,76776.2 ,1929.5,1949.9,1951.6
XS GIS Cut Line= 4
     1534494.481       246307.01     1533831.519      246817.605
     1533618.846      246995.557     1532779.001      247783.891
#Sta/Elev= 30
       0 1058.39    58.4 1056.16   136.2  1040.1   233.5 1015.49   321.1 1001.19
   418.4   976.7   544.9  940.58   651.9  900.29   729.8  878.43   788.1  855.43
   894.2  802.33   928.1  797.32   932.4  797.25   943.1  797.55  1018.5  801.21
  1123.9  801.02  1162.9  803.83  1182.4  808.25  1221.5  824.46  1299.6  873.75
  1416.7  923.77  1494.8  968.93  1533.8  986.36  1563.1   993.6    1651 1002.46
  1709.6 1001.61  1953.6  975.16  2031.7  977.27  2148.8  988.27    2266  995.11
#Mann= 3 , 0 , 0
       0      .1       0   928.1    .045       0   943.1     .05       0
Bank Sta=928.1,943.1
XS Rating Curve= 0 ,0
Exp/Cntr=0.3,0.1

Type RM Length L Ch R = 1 ,74826.2 ,287.3,283.6,279.5
XS GIS Cut Line= 4
     1533626.426      245411.177     1532667.457      245611.876
     1532489.505      245690.001     1532207.387      246124.029
#Sta/Elev= 30
       0  955.82    88.2  941.13   117.6  939.98     196  931.04   293.9  927.72
   489.9  905.06   656.4  878.08   715.2  870.66   744.6  863.15   783.8  845.25
   813.2  835.48   881.8  801.64   901.4  794.66  1028.3  790.79  1092.2  786.64
  1096.4  786.37  1107.2  787.44  1125.5  795.94  1144.9  802.67  1174.1   822.4
  1242.5  850.88  1291.3  872.54  1340.1  896.68  1379.2  912.32  1408.5  926.68
    1428  934.09  1535.5  961.04    1555  964.17  1594.1  965.43  1691.8  963.13
#Mann= 3 , 0 , 0
       0     .05       0  1092.2    .045       0  1107.2     .08       0
Bank Sta=1092.2,1107.2
XS Rating Curve= 0 ,0
Exp/Cntr=0.3,0.1

Type RM Length L Ch R = 1 ,74542.6 ,82.7,82.1,81.2
XS GIS Cut Line= 4
     1533083.038      244977.371     1532464.983      245404.454
     1532333.038      245494.732     1531774.011      245626.677
#Sta/Elev= 30
       0  948.79    58.5  932.82   107.3  922.12   175.6  901.14   273.2  875.56
   331.7  856.79   351.2     852   390.3  845.23   458.6  830.05   536.6  808.68
   556.1  804.22   634.2   797.7   692.7  791.23   779.5  789.22     823  786.21
   826.5   786.2     838   786.4   854.7  788.58   901.7   797.6   940.3  809.98
   959.8  813.87   979.3  812.32  1018.2  801.09    1028  800.21  1105.8  809.67
  1125.3  813.19  1183.7  831.56  1251.9  850.44  1339.5  887.14  1485.5  941.33
#Mann= 3 , 0 , 0
       0     .05       0     823    .045       0     838     .08       0
Bank Sta=823,838
XS Rating Curve= 0 ,0
Exp/Cntr=0.3,0.1

Type RM Length L Ch R = 1 ,74460.5 ,422.3,420.2,416.3
XS GIS Cut Line= 4
     1533048.316      244904.454     1532430.261      245331.538
     1532298.316      245421.816     1531739.288       245553.76
#Sta/Elev= 30
       0  976.69    19.5  972.32    58.5  960.29   117.1  944.27   146.4   937.5
   165.9  930.15   195.1  917.13   273.2  893.63     361  862.26   409.8  846.55
   575.6  805.62   624.4  799.24   663.4  791.32     683  789.04   798.3  788.49
   826.5  786.97   845.3  785.92  846.82 786.072   873.5  788.98   911.1  791.29
   940.3  795.93   959.8  797.81  1018.2  810.54  1057.2  823.93  1125.3  840.76
  1154.5  849.65  1251.9   885.7    1320  913.68  1388.2   937.5  1485.5  961.44
#Mann= 3 , 0 , 0
       0     .05       0   826.5    .045       0  846.82     .07       0
Bank Sta=826.5,846.82
XS Rating Curve= 0 ,0
Exp/Cntr=0.3,0.1

Type RM Length L Ch R = 1 ,74040.3 ,531.2,524.4,517.1
XS GIS Cut Line= 4
      1532800.92      244553.326      1532323.49      244943.951
     1532110.816      245134.923     1531633.386      245512.527
#Sta/Elev= 30
       0  974.91    68.5  964.65    97.9  958.23   137.1  947.81   205.6  926.56
   293.8   901.4   381.9  867.74   430.8  851.35   509.2  832.63     655  802.84
   693.1  790.81   728.1  783.93   743.1  783.58   769.3   783.5   807.4  783.71
   912.5   789.8   922.3  790.73   932.2  794.24   951.8  810.53   981.2  828.11
  1000.9  837.32  1040.2  850.62  1148.2  916.41  1197.2  940.57  1216.9  947.82
  1236.5  951.18  1295.4  953.98  1344.5  955.73    1423  956.26  1511.4  959.93
#Mann= 3 , 0 , 0
       0     .08       0   728.1    .045       0   743.1    .055       0
Bank Sta=728.1,743.1
XS Rating Curve= 0 ,0
Exp/Cntr=0.3,0.1

Type RM Length L Ch R = 1 ,73515.9 ,96.8,96.7,95.4
XS GIS Cut Line= 5
     1532405.955       244301.59     1531884.832      244683.534
     1531758.096      244867.562     1531711.221      244950.895
     1531516.777      245232.145
#Sta/Elev= 30
       0  927.65   146.8  907.38   195.8  899.82   225.2  894.36   274.1  887.54
   283.9  885.37   293.7  882.08   352.4  857.54   362.2  853.76   381.8  847.79
   499.3  817.46   597.2  795.78   616.7  794.15     685  793.27   733.5  790.17
   811.3  787.71     893783.9571   907.8  783.25  909.33783.4598     946  790.88
   955.6  795.73   974.9  811.19   984.7  817.29  1023.8  837.45  1111.7  875.02
  1131.2  882.18  1170.3  894.89  1189.8  899.95  1219.2  903.85  1307.1  909.94
#Mann= 3 , 0 , 0
       0     .05       0     893    .045       0  909.33     .06       0
Bank Sta=893,909.33
XS Rating Curve= 0 ,0
Exp/Cntr=0.3,0.1

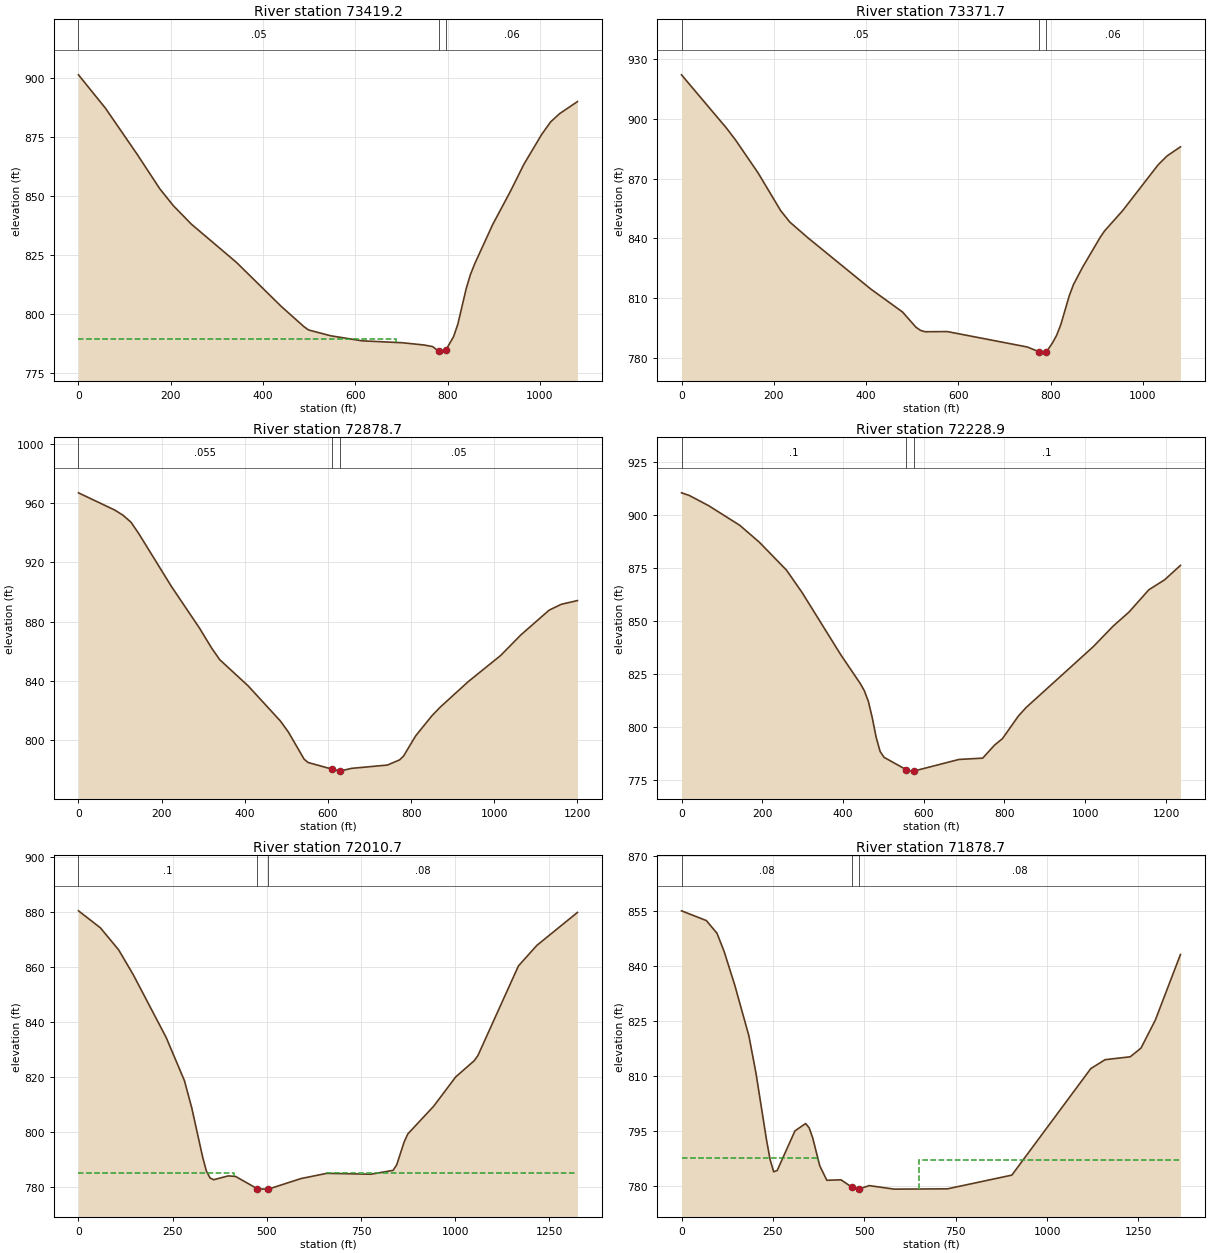
Type RM Length L Ch R = 1 ,73419.2 ,47.5,47.5,47.5
XS GIS Cut Line= 5
     1531870.944      244140.131     1531758.096      244655.756
     1531669.048      244848.638     1531615.735      244943.951
      1531497.68      245143.604
#Sta/Elev= 30
       0  901.25    58.6  887.08   127.1  867.64   175.9  853.12   205.3  845.94
   244.4   838.1   342.1  821.92   439.9  803.16   488.7  794.67   498.5  793.28
   547.1  790.79   614.7  788.68   701.6  787.87   749.4   786.9   767.6  786.24
   780.9   784.2   785.8  783.47   795.9  784.62   813.1  790.53   822.2  795.74
   840.4  810.83   849.5  816.76   859.2  821.47   897.8  837.93   936.5  852.09
   965.5  863.44  1004.1  876.08  1023.4  881.35  1042.8  884.83  1081.4  889.91
#Mann= 3 , 0 , 0
       0     .05       0   780.9    .045       0   795.9     .06       0
#XS Ineff= 2 , 0
          688.69  789.65
Permanent Ineff=
       F       F
Bank Sta=780.9,795.9
XS Rating Curve= 0 ,0
Exp/Cntr=0.3,0.1

Type RM Length L Ch R = 1 ,73371.7 ,500.9,493,484.3
XS GIS Cut Line= 5
       1531823.2      244131.451     1531710.353      244647.076
     1531621.305      244839.958     1531567.992       244935.27
     1531449.937      245134.923
#Sta/Elev= 30
       0  922.07    97.8  895.25   117.3  889.32   166.2  872.78     215  853.91
   234.6  848.23   273.7  840.36   410.5  814.55     479  803.09   508.3   795.4
     518  793.87   527.8  793.18   576.1  793.26   749.4  785.53  775.64783.0704
   785.8  782.45  789.47783.2607   794.9  784.46     804  787.58   813.1  791.45
   822.2  796.85   840.4  811.26   849.5  816.85   868.8  825.36   907.5  840.58
   917.1  843.82   955.8  853.85  1033.1  876.96  1052.4  881.39  1081.4  885.94
#Mann= 3 , 0 , 0
       0     .05       0  775.64    .045       0  789.47     .06       0
Bank Sta=775.64,789.47
XS Rating Curve= 0 ,0
Exp/Cntr=0.3,0.1

Type RM Length L Ch R = 1 ,72878.7 ,650.3,649.8,647.6
XS GIS Cut Line= 4
     1531276.036      244069.993     1531185.758       244566.52
     1531147.564      244781.798     1531005.203      245236.659
#Sta/Elev= 30
       0  966.79    87.4  955.15   106.8  951.75   126.2  947.02   145.6  939.04
   223.2  903.81   291.2  875.53   320.3  862.12   339.7  854.31   407.6   836.8
   485.3  813.08   504.7   805.6   542.7  787.25   552.2  785.02   609.2   780.6
   628.2  779.21  629.93779.3057   656.8  781.08   742.8   783.3   771.9  786.75
   781.7  789.33   810.8  802.96   849.8  816.48   869.2  822.15   937.3  839.53
  1015.1  857.12  1063.8  871.01  1131.8   887.7    1161  891.65  1199.9  894.16
#Mann= 3 , 0 , 0
       0    .055       0   609.2    .045       0  629.93     .05       0
Bank Sta=609.2,629.93
XS Rating Curve= 0 ,0
Exp/Cntr=0.3,0.1

Type RM Length L Ch R = 1 ,72228.9 ,233.7,218.2,194.2
XS GIS Cut Line= 4
     1530894.092      243938.048     1530772.564      244333.881
     1530748.258       244566.52     1530880.203      245139.437
#Sta/Elev= 30
       0  910.66    19.3  909.41    67.4  904.57   144.4   895.3   192.6  887.35
     260  874.13   298.5  863.58   394.8  834.03   443.3  820.37     453  817.04
   462.8   812.1   472.6  804.22   482.3  794.97     492  788.37   501.8  785.61
  556.83 779.774     570   779.1   575.4  779.13   687.2  784.62     746  785.24
   775.4  791.41     795  794.47   834.2   805.1   853.7  809.19  1020.3  838.01
  1069.3  847.68  1108.5  854.31  1157.5  864.82  1196.7  869.56  1235.9  876.37
#Mann= 3 , 0 , 0
       0      .1       0  556.83    .045       0   575.4      .1       0
Bank Sta=556.83,575.4
XS Rating Curve= 0 ,0
Exp/Cntr=0.3,0.1

Type RM Length L Ch R = 1 ,72010.7 ,126.2,132,145.4
XS GIS Cut Line= 5
     1530682.286      243899.854     1530550.342      244274.854
     1530609.369      244469.298     1530682.286      244712.354
     1530769.092      245174.159
#Sta/Elev= 30
       0  880.26    58.2  874.08   106.7  866.06   145.4  857.04   232.7  834.24
   281.2  818.54   300.6  808.67   329.7  790.68   339.4  785.71   349.1  783.17
   358.8  782.52   397.5  783.91   416.9  783.72     475  779.21   494.3   779.1
     504  779.11   591.1  782.96   659.3  784.84   776.4  784.52     835  785.92
   844.7  787.94   864.3   796.2   874.1  799.15   942.6  809.21  1001.3  819.89
  1050.3  825.76  1060.1  827.62  1167.8  860.24  1216.7   867.7  1324.4  879.68
#Mann= 3 , 0 , 0
       0      .1       0     475    .045       0     504     .08       0
#XS Ineff= 2 , 0
           412.5  784.91  657.91          784.82
Permanent Ineff=
       F       F
Bank Sta=475,504
XS Rating Curve= 0 ,0
Exp/Cntr=0.3,0.1

Type RM Length L Ch R = 1 ,71878.7 ,398.4,428.6,458
XS GIS Cut Line= 5
     1530567.703      243865.131     1530435.758      244240.131
     1530494.786      244434.576     1530567.703      244677.631
     1530651.036      245181.104
#Sta/Elev= 30
       0  854.94    67.9  852.29      97  848.84   116.4  843.92   145.4  834.78
   184.2  820.92   203.6  810.76   232.7   792.4   242.4  787.13   252.1  783.82
   261.8  784.19   310.3  794.98   339.4  796.97   349.1  795.81   358.8   793.1
   378.1  785.47   397.5  781.51   436.2  781.64   465.3  779.68   484.6  779.12
   513.6  780.06   581.4   779.1   727.6  779.18   903.6  782.92  1119.5  811.95
  1158.7  814.38  1227.4  815.16  1256.9  817.54  1296.1  825.18  1364.8  843.05
#Mann= 3 , 0 , 0
       0     .08       0   465.3    .045       0   484.6     .08       0
#XS Ineff= 2 , 0
          374.58  787.61  648.49          786.96
Permanent Ineff=
       F       F
Bank Sta=465.3,484.6
XS Rating Curve= 0 ,0
Exp/Cntr=0.3,0.1