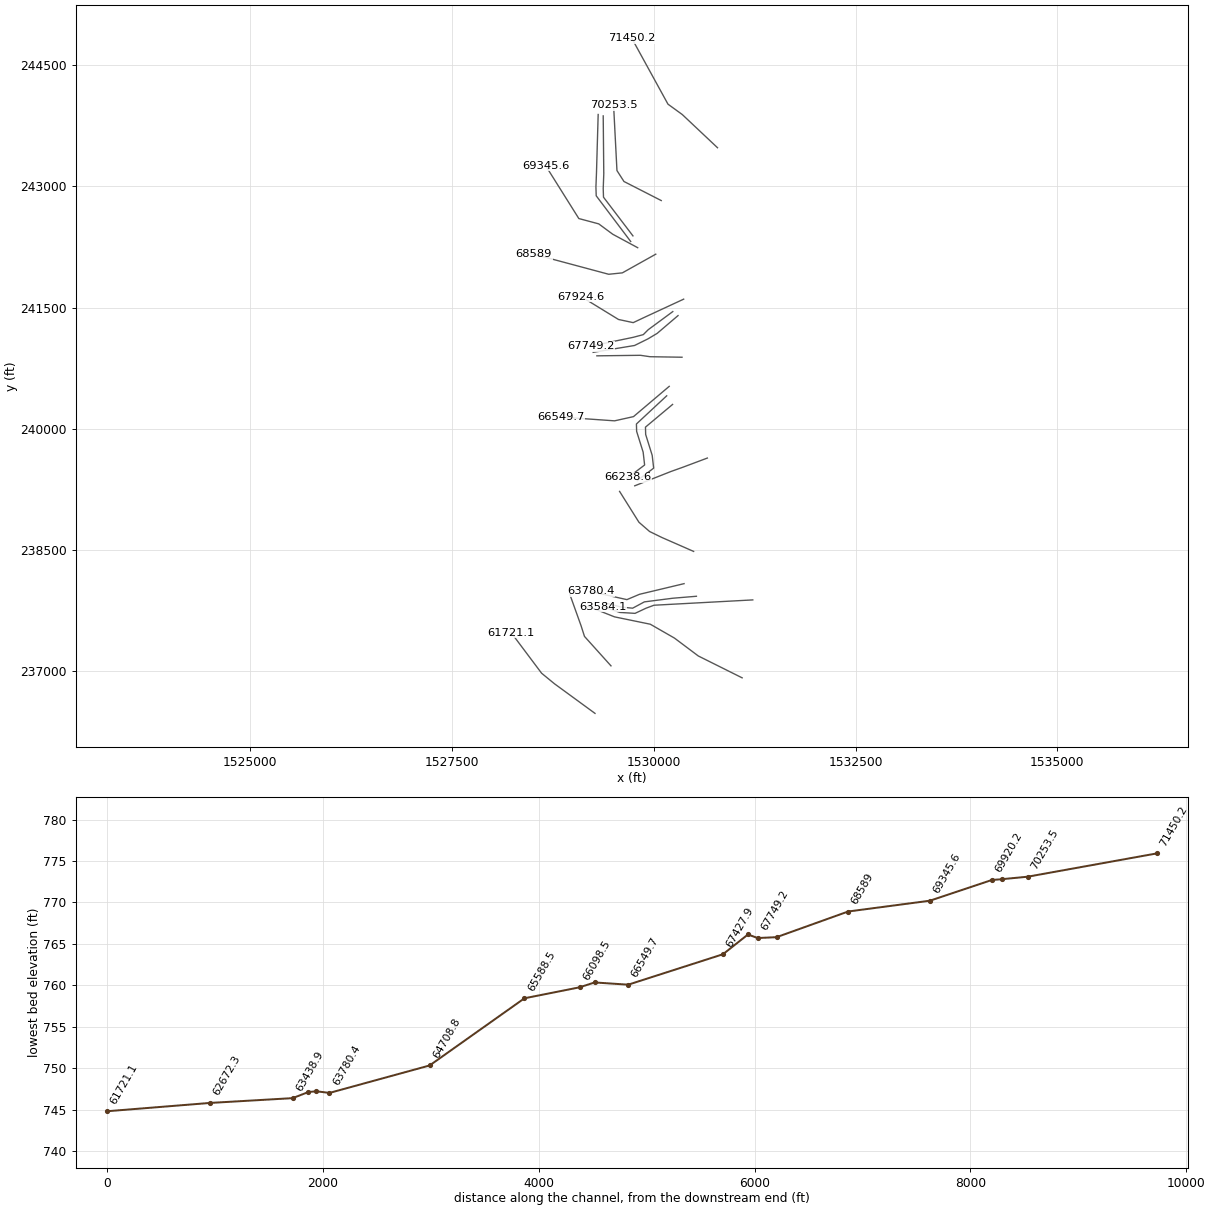
HEC-RAS study INDNCR.prj: INDNCR

--- INDNCR.g01 (geometry) --- (continued)

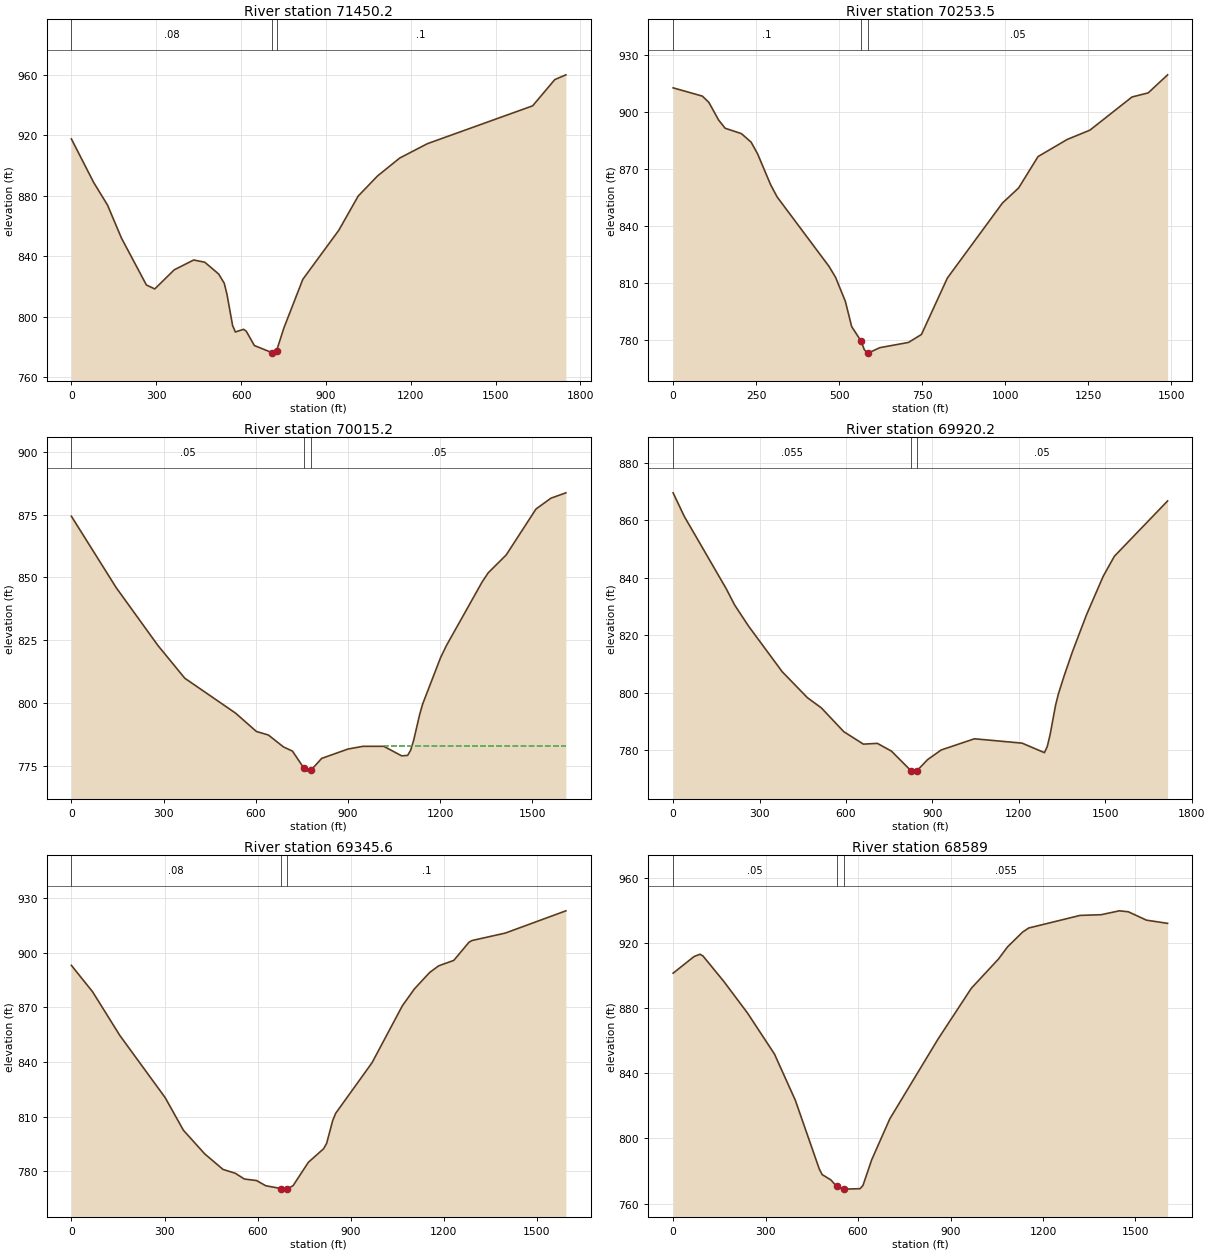
Type RM Length L Ch R = 1 ,71450.2 ,1204.3,1196.7,1188.3
XS GIS Cut Line= 4
     1530790.054       243479.03     1530353.727      243890.088
     1530176.644       244018.56     1529728.856       244833.92
#Sta/Elev= 30
       0   917.7    78.6  888.95   127.8   873.9   176.9  852.12   265.3  821.01
   294.8   818.4   363.6  831.04   432.4  837.56   471.7  836.08   520.8  828.26
   540.5  822.17   550.3  814.71     570  794.22   579.8  789.91     609  791.68
   618.5  790.39     647  780.95   710.5  776.13   713.6  775.91   725.5  777.47
   751.6  792.67   818.2  824.72   945.5  857.22  1014.1  879.86  1082.6   893.2
    1161  905.05  1258.9  914.55    1631   939.6  1709.3  956.97  1748.5  960.12
#Mann= 3 , 0 , 0
       0     .08       0   710.5    .045       0   725.5      .1       0
Bank Sta=710.5,725.5
XS Rating Curve= 0 ,0
Exp/Cntr=0.3,0.1

Type RM Length L Ch R = 1 ,70253.5 ,251.8,238.3,223
XS GIS Cut Line= 4
      1530093.31      242824.695     1529631.505      243060.806
     1529544.699      243196.222     1529503.033      244004.671
#Sta/Elev= 30
       0  912.67    88.1  908.32   107.6  905.03     137  895.75   156.6  891.42
   205.5   888.6   234.9   884.1   254.4  877.93   293.6  861.72   313.2  855.28
   469.7  818.67   489.3  812.93   518.7  800.33   537.6  787.09     566  779.44
   575.4  775.03   584.9   773.1  586.99773.1264   622.7  775.98   708.8  778.74
   747.8  782.92   825.8   812.6   991.6  852.06  1040.4  860.01  1098.9  876.52
  1186.7  885.52    1255  890.41  1381.8  907.86  1430.5  910.02    1489  919.52
#Mann= 3 , 0 , 0
       0      .1       0     566    .045       0  586.99     .05       0
Bank Sta=566,586.99
XS Rating Curve= 0 ,0
Exp/Cntr=0.3,0.1

Type RM Length L Ch R = 1 ,70015.2 ,94.8,95,96
XS GIS Cut Line= 5
     1529742.616      242387.195     1529378.033      242866.361
      1529374.56         242974.     1529381.505      243154.556
      1529374.56      243873.306
#Sta/Elev= 30
       0  874.31   145.7   845.9   281.6  822.85     369  809.81   534.1  795.92
   602.1   788.6   641.3  787.17   690.2  782.44   719.3  780.79   757.3   773.9
   766.8   772.8  779.13773.0786   814.4  777.86   900.2   781.6   948.8  782.68
  1016.8  782.68    1075  778.88  1094.5  779.08  1104.2  781.17  1113.9  785.06
  1133.3  795.28    1143  799.48  1201.3  817.94  1220.7  822.86  1337.3  848.26
  1356.7   851.8    1415  858.89  1512.1   877.2  1560.7  881.51  1609.3  883.64
#Mann= 3 , 0 , 0
       0     .05       0   757.3     .04       0  779.13     .05       0
#XS Ineff= 2 , 0
                         1015.68          782.82
Permanent Ineff=
       F       F
Bank Sta=757.3,779.13
XS Rating Curve= 0 ,0
Exp/Cntr=0.3,0.1

Type RM Length L Ch R = 1 ,69920.2 ,544,574.7,601.2
XS GIS Cut Line= 5
     1529714.838       242317.75     1529287.755      242883.722
     1529284.283      242991.361     1529291.227      243171.917
      1529312.06      243890.667
#Sta/Elev= 30
       0   869.5    38.8   861.3   184.5  836.12   213.7  830.46   262.2  823.09
   378.8  807.26   466.2  798.24   514.8  794.68   592.5  786.42   660.5  782.09
     709  782.36     758  779.65   826.2  772.79   835.8   772.7  846.25  772.81
   883.3   776.7   930.8  780.07    1046  783.95  1211.2  782.44  1288.9  779.13
  1298.6  781.19  1308.4  785.29  1327.8  795.73  1337.5  799.58  1356.9  805.71
  1386.1  814.22  1434.7  827.02    1493  840.49  1531.8  847.45  1716.5  866.68
#Mann= 3 , 0 , 0
       0    .055       0   826.2    .045       0  846.25     .05       0
Bank Sta=826.2,846.25
XS Rating Curve= 0 ,0
Exp/Cntr=0.3,0.1

Type RM Length L Ch R = 1 ,69345.6 ,745.6,756.5,767.3
XS GIS Cut Line= 5
     1529801.644      242240.783     1529492.616      242407.449
     1529319.005      242535.921     1529072.477      242601.894
     1528662.755      243254.671
#Sta/Elev= 30
       0  892.98    68.3  878.48     156  854.54   302.3  820.36   360.9   802.5
   429.6  789.53   488.6  781.01   527.8  778.92   557.3  775.74   596.5  774.92
     626  772.07     675  770.53   694.7   770.2  695.71770.2433   714.3  772.14
   763.4  784.92   812.5  792.36   822.3  795.32   841.8  807.82   851.6  811.85
   968.6  839.57  1066.2  870.79  1105.2  880.08    1154  889.04  1183.2  892.72
    1232  895.71  1280.8  905.66  1290.6   906.6  1397.9  910.68    1593  922.89
#Mann= 3 , 0 , 0
       0     .08       0     675    .045       0  695.71      .1       0
Bank Sta=675,695.71
XS Rating Curve= 0 ,0
Exp/Cntr=0.3,0.1

Type RM Length L Ch R = 1 ,68589   ,656.2,664.4,672.2
XS GIS Cut Line= 4
     1530025.297      242160.453      1529611.54      241929.151
     1529442.269      241911.789     1528514.881      242160.453
#Sta/Elev= 30
       0  901.37    67.7  911.55    87.1  912.99    96.7  911.97   164.5  896.31
   241.8   876.8   328.9  851.73   396.6  823.37     474  781.37   483.5  777.82
   511.8  774.56   530.7  770.53   549.6   768.9  554.19768.9097   606.4  769.16
   615.8  771.09   644.2  786.88     703  812.02   859.7  861.02   967.5  892.11
  1055.7  910.09  1085.1  917.54    1134  926.61  1153.6  929.08  1320.2  936.81
  1388.8  937.24  1447.6  939.62    1477  939.03  1535.8  933.89  1604.3  931.94
#Mann= 3 , 0 , 0
       0     .05       0   530.7     .04       0  554.19    .055       0
Bank Sta=530.7,554.19
XS Rating Curve= 0 ,0
Exp/Cntr=0.3,0.1

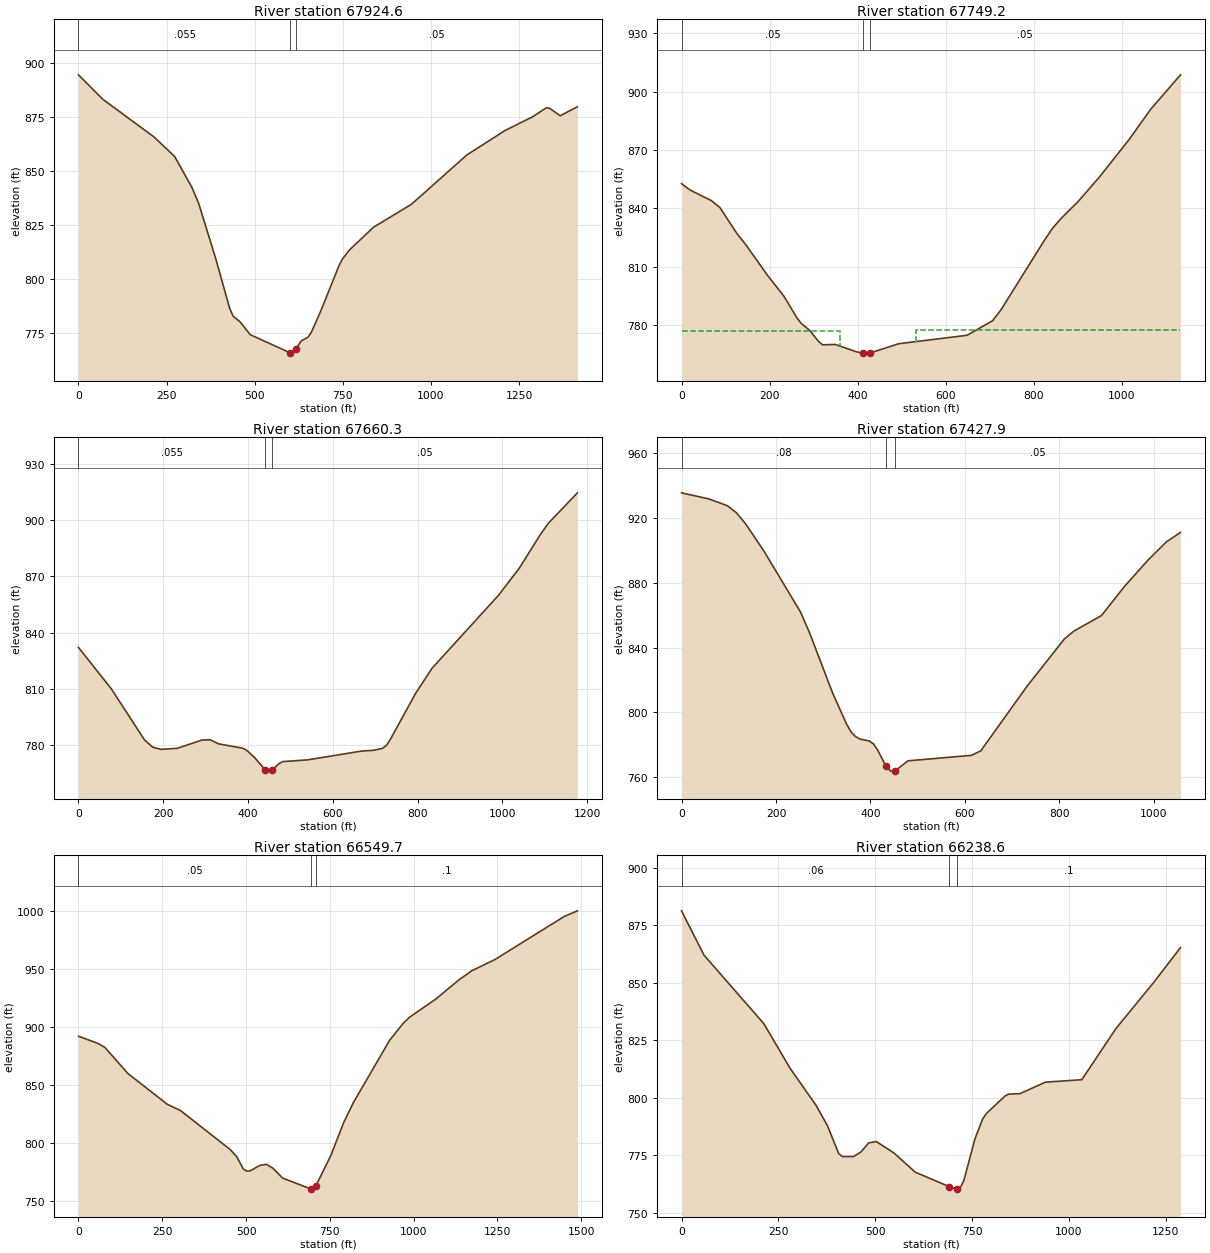
Type RM Length L Ch R = 1 ,67924.6 ,167.3,175.5,183.3
XS GIS Cut Line= 5
     1530371.088       241603.63     1529893.658      241382.276
     1529746.088      241312.831     1529563.797      241351.894
     1529103.727      241634.012
#Sta/Elev= 30
       0  894.59    68.2  883.38   214.4  865.82   272.9  856.78   321.6  842.55
   341.1     835   389.8  809.28   428.8  786.54   438.5  782.93     458  780.33
   487.3  774.34   601.1   765.9     603   765.8   616.1  767.61   631.8  771.45
     651  773.16   660.6  775.44   689.3  786.07   738.4  806.08   748.2  809.19
   767.8   813.4   836.5  824.01   944.5  834.68  1101.5  857.48  1209.4  868.76
  1287.9  875.14  1327.1  879.34    1337  879.08  1366.4  875.65  1415.4  879.83
#Mann= 3 , 0 , 0
       0    .055       0   601.1     .04       0   616.1     .05       0
Bank Sta=601.1,616.1
XS Rating Curve= 0 ,0
Exp/Cntr=0.3,0.1

Type RM Length L Ch R = 1 ,67749.2 ,94.4,88.9,83.4
XS GIS Cut Line= 5
     1530236.235      241449.516     1529931.635      241224.941
     1529870.871      241164.177     1529749.343      241131.625
     1529217.659      241020.947
#Sta/Elev= 30
       0  852.71    19.4  849.43    67.9  843.98    87.3   840.4   126.2  826.98
   145.6   821.5   194.1     806   232.9  794.85     262  783.83   271.7  780.99
   291.1  777.39   310.5  771.92   320.2  769.96   349.3  770.15   397.5  766.36
   412.7  765.71   416.6   765.7   427.7  765.74   493.4  770.53   648.4  774.85
   706.6  782.34     726  788.05   822.9  823.14   842.3  829.68   861.7  834.72
   900.5  843.42     949  856.04  1016.9  875.42  1065.4  890.81  1133.3  908.56
#Mann= 3 , 0 , 0
       0     .05       0   412.7    .045       0   427.7     .05       0
#XS Ineff= 2 , 0
          359.57  777.08  531.77          777.74
Permanent Ineff=
       F       F
Bank Sta=412.7,427.7
XS Rating Curve= 0 ,0
Exp/Cntr=0.3,0.1

Type RM Length L Ch R = 1 ,67660.3 ,248,232.3,216.5
XS GIS Cut Line= 5
     1530301.339      241400.037     1530042.312      241179.368
     1529929.465      241112.093     1529762.364      241029.628
     1529250.211      240944.993
#Sta/Elev= 30
       0   832.1    77.8   809.9   155.6  782.84     175  778.91   194.4  777.75
   233.3   778.3   291.7  782.74   311.1  782.81   330.6  780.66   387.2  778.37
   396.6  777.29   415.4  773.37  440.32766.8884   452.9  766.13   457.4  766.85
   471.7  769.87   481.5   771.2   540.3  772.13   667.8  776.82   697.2  777.25
   716.8  778.27   726.6   779.8   736.4  783.33   795.1  807.53   834.3  821.04
     991   859.9    1040  874.37    1089  892.06  1108.5  898.29  1177.1  914.52
#Mann= 3 , 0 , 0
       0    .055       0  440.32    .045       0   457.4     .05       0
Bank Sta=440.32,457.4
XS Rating Curve= 0 ,0
Exp/Cntr=0.3,0.1

Type RM Length L Ch R = 1 ,67427.9 ,870.5,878.2,885.6
XS GIS Cut Line= 4
     1530350.472      240884.229     1529953.336      240890.739
     1529836.149        240908.1     1529295.784       240901.59
#Sta/Elev= 30
       0  935.64    58.1  931.87    96.9   927.7   116.2  923.34   135.6   916.5
   174.4  899.69   251.9     862   271.2  849.08   319.7  812.07   348.8  793.15
   358.4  788.19   368.1  785.12   377.8  783.54   397.2  782.39   406.3  780.56
   415.4  776.63   432.9  766.68   442.8  763.74   451.9  763.84   479.2   770.1
   613.9  773.49   633.6  776.33   731.8  816.35   810.4  845.38   830.1  850.17
     889  859.86   938.2  878.01   987.3  894.05  1026.6  905.44  1056.1  911.17
#Mann= 3 , 0 , 0
       0     .08       0   432.9    .045       0   451.9     .05       0
Bank Sta=432.9,451.9
XS Rating Curve= 0 ,0
Exp/Cntr=0.3,0.1

Type RM Length L Ch R = 1 ,66549.7 ,258.7,311.1,357.2
XS GIS Cut Line= 4
     1530192.052      240523.552     1529749.343      240148.552
     1529514.968      240096.468     1528848.302      240143.343
#Sta/Elev= 30
       0  892.17      59  885.82    78.7   882.5   147.5  859.92   265.5  833.26
   304.8  827.85   452.4  794.33     472  788.14   491.7  777.49   501.5   775.7
   511.4  775.73   540.8  780.52   560.5   781.5   580.2   778.1     609  769.62
   693.5  760.19   695.4  760.07   708.5  763.03     753  789.19   791.5  817.76
   820.3  834.89   928.4  888.71   967.7  902.94   987.4  908.51    1066  924.24
  1134.8   940.8  1174.1   948.8  1242.9  958.45  1449.3  995.63  1488.6 1000.47
#Mann= 3 , 0 , 0
       0     .05       0   693.5    .045       0   708.5      .1       0
Bank Sta=693.5,708.5
XS Rating Curve= 0 ,0
Exp/Cntr=0.3,0.1

Type RM Length L Ch R = 1 ,66238.6 ,142.9,140.1,135.8
XS GIS Cut Line= 6
     1530160.802      240406.364     1529785.802      240057.406
     1529788.406       239966.26     1529869.135      239708.447
     1529887.364      239549.593     1529684.239      239395.947
#Sta/Elev= 30
       0  881.33      58  862.08   212.6  832.26   280.3  812.89   347.9  796.64
   376.9  787.88   405.9  775.75   415.6   774.5   444.6  774.52   463.9  776.59
   483.2  780.43   502.6  781.05   548.7  776.03   603.4  767.72   691.1  761.44
   709.6  760.34  712.11760.4655   719.2  760.82   728.9  764.08   757.8   782.3
   777.1   790.7   786.8  793.14     835   800.8   844.6  801.65   873.6  801.83
   939.4  806.84  1033.5  807.92  1121.6  830.14  1219.6   850.3  1288.2  865.34
#Mann= 3 , 0 , 0
       0     .06       0   691.1    .045       0  712.11      .1       0
Bank Sta=691.1,712.11
XS Rating Curve= 0 ,0
Exp/Cntr=0.3,0.1

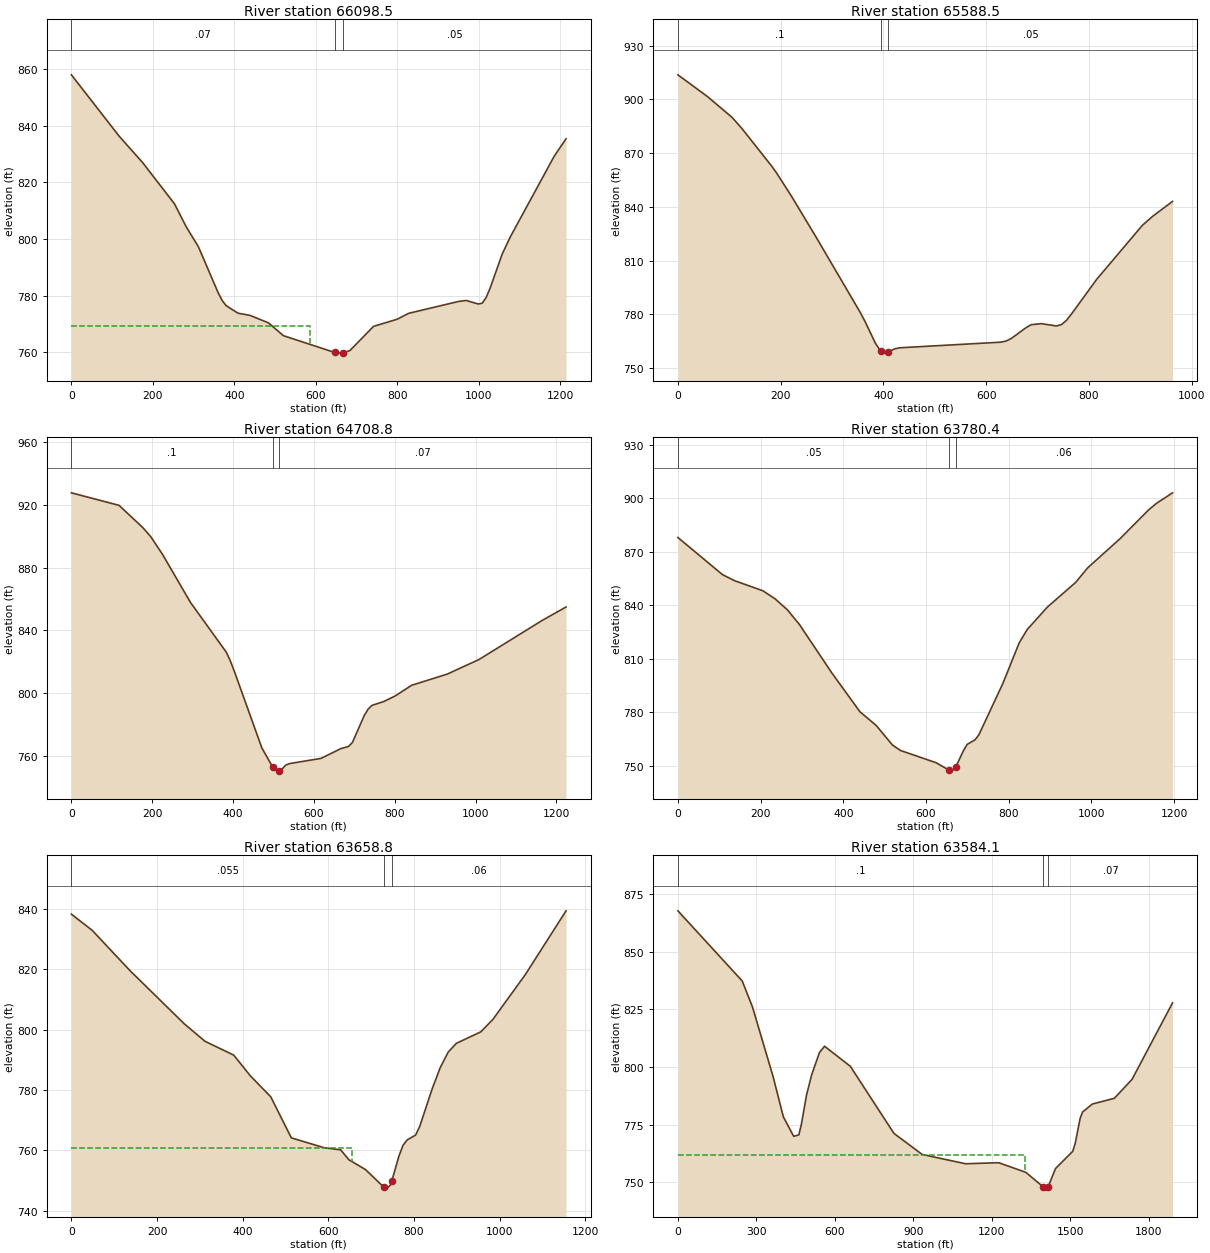
Type RM Length L Ch R = 1 ,66098.5 ,557.2,510.1,467.4
XS GIS Cut Line= 6
     1530233.718      240299.593     1529897.781      240018.343
     1529900.385      239927.197     1529981.114      239669.385
     1529999.343      239510.531     1529796.218      239356.885
#Sta/Elev= 30
       0  857.87   116.8  836.32   175.2  826.86   253.1  812.38   282.4  804.14
   311.6  797.29   360.2  781.05     370  778.32   379.7   776.5   408.9  773.83
   438.1  773.07   483.7  770.43   520.2  765.91   646.4  759.98   664.4  759.75
  666.37759.7869   683.7  760.68   741.6  769.19   799.5  771.69   827.7  773.78
     950  777.96   969.2  778.31   998.6  777.07  1008.3  777.36  1018.1  779.39
  1027.9  782.73  1057.3  794.66  1076.9  800.63  1184.7   829.1    1214  835.32
#Mann= 3 , 0 , 0
       0     .07       0   646.4    .045       0  666.37     .05       0
#XS Ineff= 2 , 0
          585.28  769.48
Permanent Ineff=
       F       F
Bank Sta=646.4,666.37
XS Rating Curve= 0 ,0
Exp/Cntr=0.3,0.1

Type RM Length L Ch R = 1 ,65588.5 ,896.6,879.7,860.2
XS GIS Cut Line= 4
     1530664.274      239635.531     1530358.718      239520.947
     1530212.885      239468.864     1529764.968      239291.781
#Sta/Elev= 30
       0  913.65    57.6  901.51   105.6  889.87   124.8  883.64   182.4  862.77
     192  858.94   220.8  846.08   268.8  823.23   355.4  780.89     365  775.65
   384.4  763.97   394.7  759.48   403.8  758.43   409.7  759.19   423.1  760.93
   432.8  761.42   628.6  764.54   638.5  765.14   648.3  766.46   677.8  772.68
   687.6  774.28   707.3  774.88   736.8  773.59   746.6  774.34   756.4  776.73
   766.2  780.29   815.4  799.67   903.9  829.66   923.5  834.61   962.8  843.06
#Mann= 3 , 0 , 0
       0      .1       0   394.7    .045       0   409.7     .05       0
Bank Sta=394.7,409.7
XS Rating Curve= 0 ,0
Exp/Cntr=0.3,0.1

Type RM Length L Ch R = 1 ,64708.8 ,908.1,928.4,947.2
XS GIS Cut Line= 5
     1530494.135      238479.281     1530098.302      238652.892
     1529948.996      238725.809     1529817.052      238840.392
     1529577.468      239222.336
#Sta/Elev= 30
       0  927.76   117.9  919.78   176.8  905.58   196.5  899.76   225.9  888.36
   294.7  857.87   383.1  826.24   392.9  820.88   402.8  814.28   471.3  765.14
   498.5  752.75   510.4  750.32   513.5  750.64   520.2  751.32     530   754.1
   539.8  755.12   617.8  758.44   666.4  764.63   685.8  766.06   695.5  768.62
   724.6  785.72   734.3  789.87     744  792.27   773.2   794.7   802.6  798.45
   841.8  805.04     930  812.18  1008.4  821.44  1165.2  846.44    1224  854.96
#Mann= 3 , 0 , 0
       0      .1       0   498.5    .045       0   513.5     .07       0
Bank Sta=498.5,513.5
XS Rating Curve= 0 ,0
Exp/Cntr=0.3,0.1

Type RM Length L Ch R = 1 ,63780.4 ,119.5,121.6,123.6
XS GIS Cut Line= 4
      1530376.08      238079.975     1529823.996      237948.031
     1529667.746      237882.059      1529219.83      237982.753
#Sta/Elev= 30
       0  878.02   107.6  857.23     137   853.8   205.5  848.15   234.9  843.65
   264.2   837.6   293.6  829.34   371.9   802.2   440.4  780.26   479.6  772.63
   518.7  761.69   538.3  758.59   624.2  751.75   656.8  747.41   661.9  747.01
   671.8  749.21   690.1  758.26   699.6  762.02   718.4  764.53   727.8  767.32
   786.1  796.26   825.2  818.82   844.7  826.39   893.5  838.98   961.9  852.82
   991.2  861.04  1069.4  877.37  1137.7  893.32  1157.3  897.15  1196.3  903.07
#Mann= 3 , 0 , 0
       0     .05       0   656.8    .045       0   671.8     .06       0
Bank Sta=656.8,671.8
XS Rating Curve= 0 ,0
Exp/Cntr=0.3,0.1

Type RM Length L Ch R = 1 ,63658.8 ,75.9,74.7,73.5
XS GIS Cut Line= 6
     1530528.857      237923.725     1530237.191       237899.42
      1529884.76      237854.281     1529738.927      237776.156
     1529597.219      237789.358     1529404.667      237840.522
#Sta/Elev= 30
       0  838.16    48.8  832.79   136.6  819.52   263.4  801.92   311.9  796.12
   379.1  791.54   417.5  784.75   465.5  777.75   513.6  764.17   590.4   760.9
   628.8   760.2     648  756.92   686.9  753.67  729.56747.8589   735.6  747.21
   745.3  748.65   748.3  749.96   764.8  758.14   774.5  761.73   784.2  763.51
   803.7  765.07   813.4  767.94   841.9  780.16   860.9  787.28   879.8  792.52
   898.8  795.43   955.8  799.22   984.2  803.34  1060.1   818.2    1155  839.27
#Mann= 3 , 0 , 0
       0    .055       0  729.56    .045       0   748.3     .06       0
#XS Ineff= 2 , 0
          655.75  760.88
Permanent Ineff=
       F       F
Bank Sta=729.56,748.3
XS Rating Curve= 0 ,0
Exp/Cntr=0.3,0.1

Type RM Length L Ch R = 1 ,63584.1 ,160.9,145.2,136.2
XS GIS Cut Line= 6
     1531227.208      237878.586     1530002.816      237812.614
     1529905.593      237776.156     1529768.441       237711.92
     1529581.751      237723.335     1529370.813      237793.647
#Sta/Elev= 30
       0  867.69   245.9  837.29   285.2  825.99   363.9  795.86   403.2  778.41
   442.6     770   462.3  770.61   472.1  775.23   491.8  787.93   511.4  796.66
     541  806.26   560.6  809.02     659  800.35     826  771.25   933.9  762.13
  1099.6   758.1  1226.3  758.56  1330.1  754.39  1396.9  748.04  1405.8  747.11
  1415.3  748.09  1443.7  756.04  1509.6  763.51    1519  766.98  1537.7  777.74
    1547  780.51  1584.4  783.98  1668.6  786.46  1736.3  794.69    1891   827.8
#Mann= 3 , 0 , 0
       0      .1       0  1396.9    .045       0  1415.3     .07       0
#XS Ineff= 2 , 0
         1325.81  762.07
Permanent Ineff=
       F       F
Bank Sta=1396.9,1415.3
XS Rating Curve= 0 ,0
Exp/Cntr=0.3,0.1

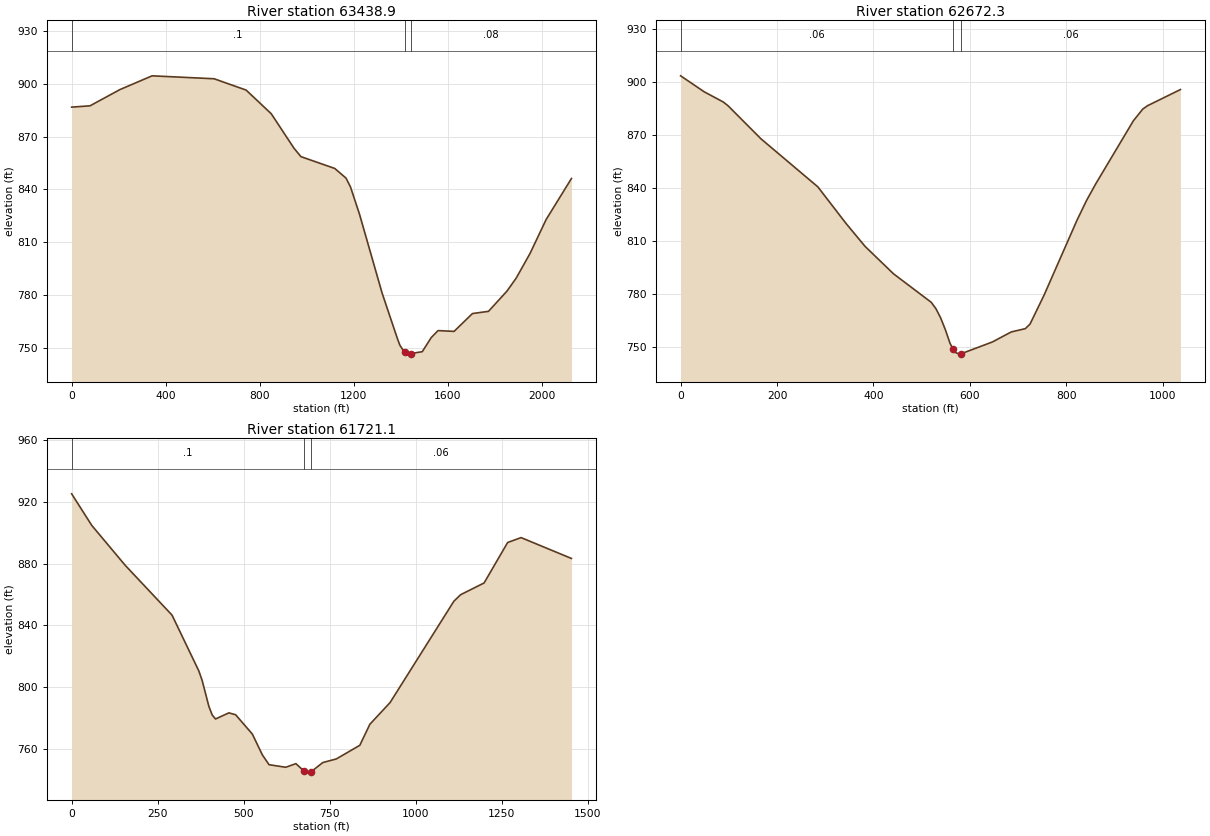
Type RM Length L Ch R = 1 ,63438.9 ,789.4,766.7,732.4
XS GIS Cut Line= 6
     1531095.264      236913.309     1530552.573      237183.934
     1530257.156      237405.496     1529957.677      237577.371
     1529514.968      237668.517     1529186.843      237798.725
#Sta/Elev= 30
       0  886.71    78.2  887.45   205.4  896.67   342.3  904.49   606.4  902.82
   742.5  896.38   849.4  882.94   946.5  863.29   975.7  858.57  1119.6  851.87
  1167.5  846.38  1186.7  841.31  1225.1  825.79    1321  781.09  1387.5  754.69
    1397  751.38  1416.5   747.4  1431.5  746.38  1444.5  746.72    1492  747.77
  1530.1  755.77  1559.1  759.75  1627.4   759.3  1705.5  769.43  1773.8  770.69
  1852.2  782.15  1891.5  789.53  1950.3   803.5    2019  822.83  2126.8  846.16
#Mann= 3 , 0 , 0
       0      .1       0  1416.5    .045       0  1444.5     .08       0
Bank Sta=1416.5,1444.5
XS Rating Curve= 0 ,0
Exp/Cntr=0.3,0.1

Type RM Length L Ch R = 1 ,62672.3 ,938.2,951.2,963.9
XS GIS Cut Line= 4
     1529470.698      237061.746     1529142.573      237426.329
     1529100.906      237556.538     1528962.885      237941.954
#Sta/Elev= 30
       0  903.51      49  894.44    88.3  888.71    98.1  886.61   166.8  867.77
   284.5  840.62   343.4  819.74   382.6  806.85   441.4  791.35   519.8  775.16
   529.6   771.5   539.3  766.34   549.1  759.62   558.8   751.9   564.7  748.87
   568.6  746.86   578.4   745.8  582.07746.0545   646.7   752.7   685.7  758.37
   714.9  760.24   724.7  762.84   753.9  779.29   822.2  821.74   841.6  832.72
   861.1  842.35   939.1  878.07   958.6   884.7   968.4  886.58  1036.6  895.73
#Mann= 3 , 0 , 0
       0     .06       0   564.7    .045       0  582.07     .06       0
Bank Sta=564.7,582.07
XS Rating Curve= 0 ,0
Exp/Cntr=0.3,0.1

Type RM Length L Ch R = 1 ,61721.1 ,915.3,902.2,888.4
XS GIS Cut Line= 4
     1529272.781      236473.204     1528770.177      236840.392
     1528611.323        236970.6     1528236.323        237470.6
#Sta/Elev= 30
       0  925.32    58.4  904.86   155.6  878.97   291.8  846.64   369.6  810.48
   379.3  804.31   398.8  787.51   408.5  781.91   418.2  779.27   457.1  783.25
   476.6  782.02   525.2   769.5   554.4  755.97   573.8  749.62   622.4  747.95
   651.8   750.3   675.8  745.42   690.8   744.8  695.52744.9431     730  751.02
   769.2  753.34   837.6   762.2   866.9  775.86   925.5   789.9    1111  855.64
  1130.6  859.87  1198.9  867.51  1267.3  893.74  1306.4  896.92  1452.8   883.4
#Mann= 3 , 0 , 0
       0      .1       0   675.8    .045       0  695.52     .06       0
Bank Sta=675.8,695.52
XS Rating Curve= 0 ,0
Exp/Cntr=0.3,0.1