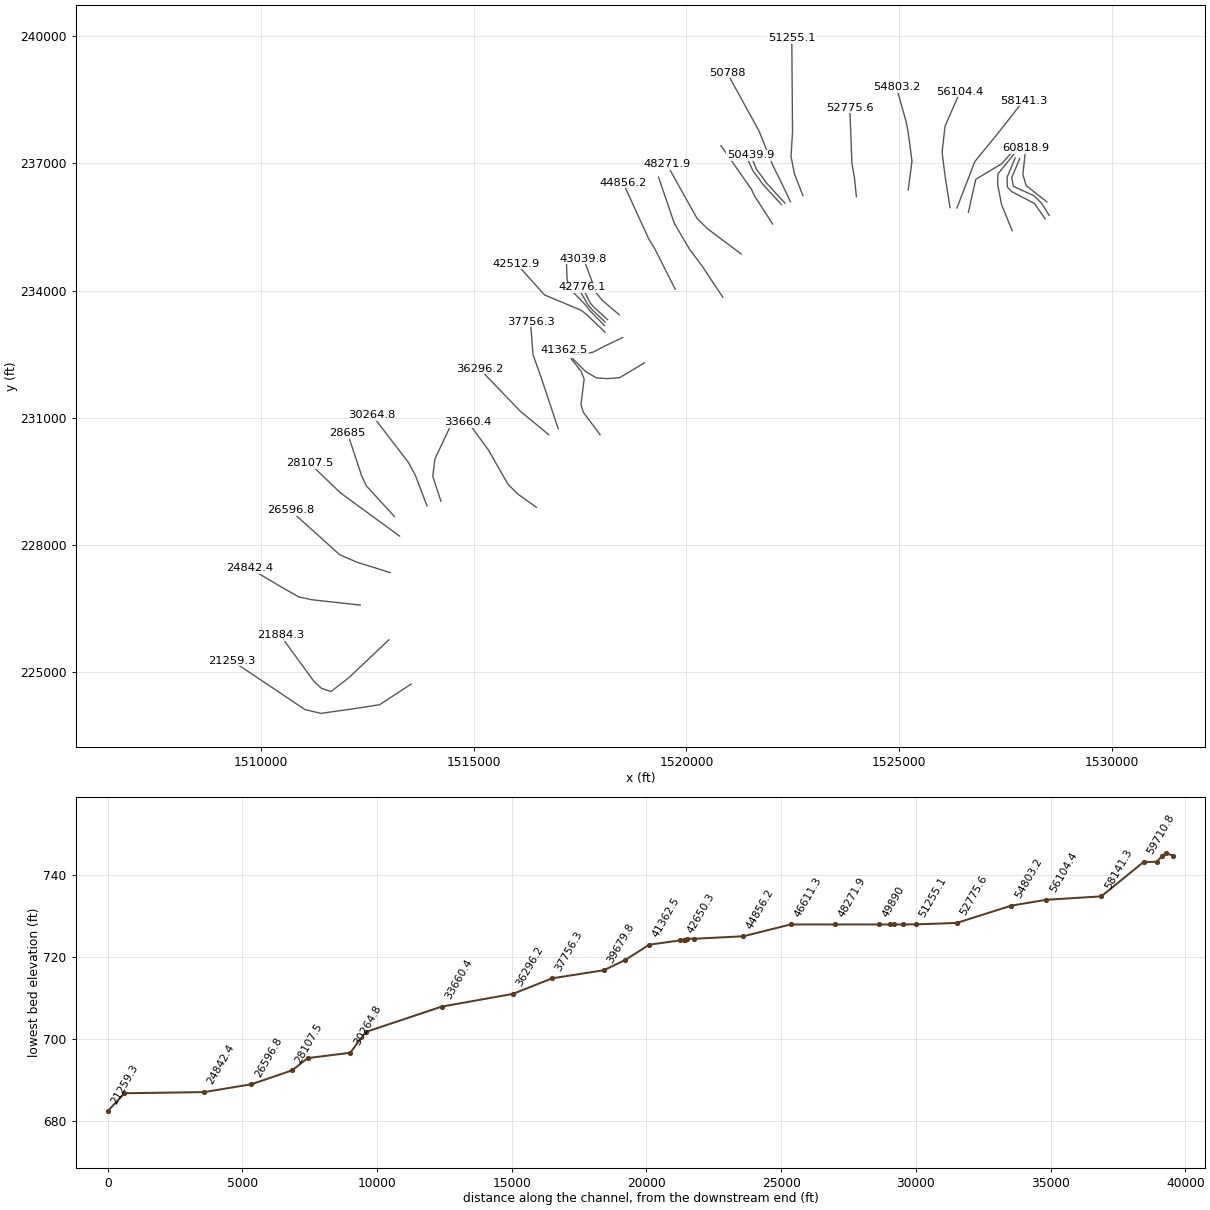
HEC-RAS study INDNCR.prj: INDNCR

--- INDNCR.g01 (geometry) --- (continued)

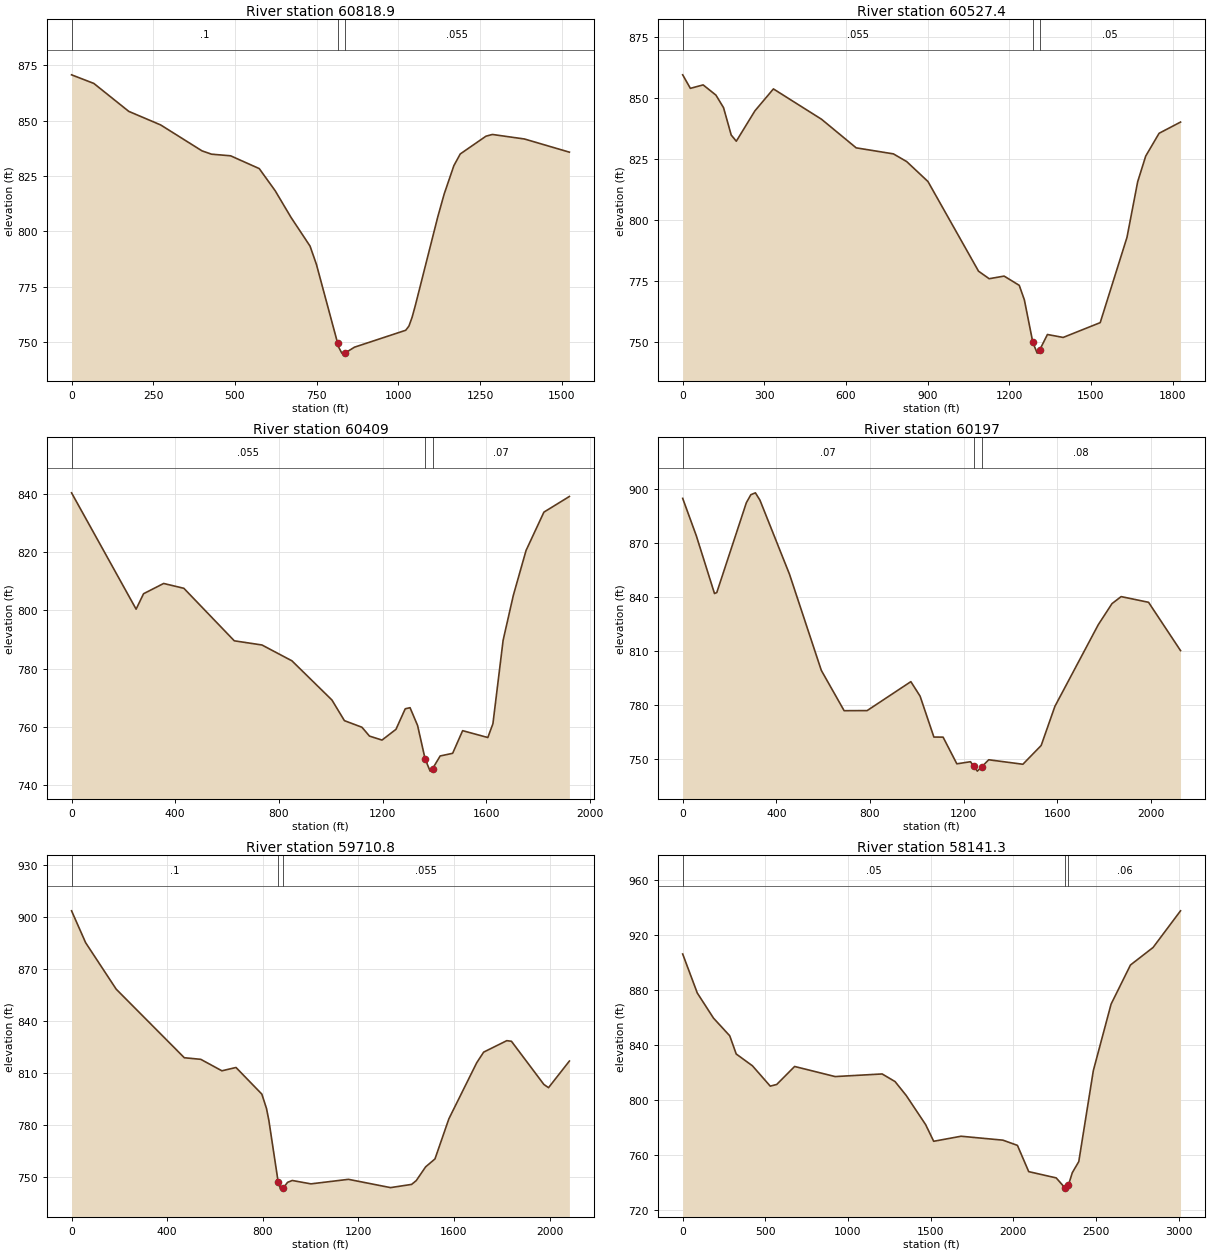
Type RM Length L Ch R = 1 ,60818.9 ,297.6,291.4,285.2
XS GIS Cut Line= 4
     1528479.291      236091.434     1527989.708       236476.85
     1527911.583      236737.267     1527979.291      237362.267
#Sta/Elev= 30
       0  870.77    68.2  866.88   175.2  854.23   272.6  848.11   399.2  836.37
   428.4  834.87   486.8  834.13   574.4  828.35   623.1  818.35   671.6  806.28
   729.9  793.28   749.3  785.06   813.9   749.6   817.3  747.62     827  744.89
   836.7  744.86  837.69744.9549   865.8  747.55  1022.7   755.2  1032.5  757.09
  1042.3  761.12  1052.1  766.42  1120.9  806.56  1140.5  816.89    1170  829.66
  1189.6  834.97  1268.2     843  1287.9  843.79  1386.1  841.74  1523.6  835.78
#Mann= 3 , 0 , 0
       0      .1       0   813.9    .045       0  837.69    .055       0
Bank Sta=813.9,837.69
XS Rating Curve= 0 ,0
Exp/Cntr=0.3,0.1

Type RM Length L Ch R = 1 ,60527.4 ,121.9,118.5,115.1
XS GIS Cut Line= 6
     1528531.085      235773.581     1528356.027      236056.711
     1528175.472      236237.267     1527689.361      236459.489
     1527649.141      236665.218     1527838.666      237115.739
#Sta/Elev= 30
       0  859.41    28.2  853.87    75.1  855.28     122  851.12   150.1  845.96
   178.3  834.75     197  832.21   265.2  844.62   333.3  853.64   510.1  841.21
   637.5  829.49   774.2  827.02     823  823.87   901.1  815.71    1087  778.96
  1126.1  775.87  1181.1  776.94  1236.6  773.16  1255.4  767.22  1286.5   749.8
  1302.5  745.38  1311.9  746.72  1340.2  753.01    1398  751.81  1534.1  757.87
  1632.5  792.83  1671.8  815.62  1701.3  826.12  1750.5  835.46  1829.2  840.05
#Mann= 3 , 0 , 0
       0    .055       0  1286.5    .045       0  1311.9     .05       0
Bank Sta=1286.5,1311.9
XS Rating Curve= 0 ,0
Exp/Cntr=0.3,0.1

Type RM Length L Ch R = 1 ,60409   ,209.5,211.9,214.3
XS GIS Cut Line= 6
     1528437.335      235692.851     1528183.863      236055.699
     1527643.933      236338.685      1527546.71      236446.324
     1527540.634      236676.069     1527730.159       237126.59
#Sta/Elev= 30
       0  840.38   249.1  800.44   277.8  805.74   355.4  809.26   433.3   807.6
   627.9  789.57   734.6  788.14   850.3   782.7  1004.6  769.25  1052.8  762.16
  1120.5  759.89  1149.5  756.86  1197.8  755.49  1251.6  759.17  1287.4  766.23
    1306  766.61  1335.1   760.5  1364.1  749.03  1383.5  744.83  1393.1   745.7
  1422.2  750.03  1470.4  750.95  1508.9  758.72  1606.1  756.37  1625.8  761.12
  1665.1  789.76  1704.5  805.18  1753.6  820.59  1822.5  833.75  1920.8  839.13
#Mann= 3 , 0 , 0
       0    .055       0  1364.1    .045       0  1393.1     .07       0
Bank Sta=1364.1,1393.1
XS Rating Curve= 0 ,0
Exp/Cntr=0.3,0.1

Type RM Length L Ch R = 1 ,60197   ,508.5,486.3,463.5
XS GIS Cut Line= 5
     1527661.583       235414.35     1527411.583      236025.461
     1527317.833        236508.1     1527324.777      236751.156
     1527782.821      237322.192
#Sta/Elev= 30
       0   894.6    58.3  873.84   135.9  841.84   145.6  842.34   271.9  892.14
   291.3  896.64   310.7  897.67   330.1  893.61   456.4  852.51   592.3  799.21
   689.8  776.85   788.1   776.9   974.9  792.95  1014.3  784.93  1073.3  762.23
  1112.6  762.18  1171.4  747.38  1229.7  748.54    1243  746.12  1258.9  743.33
  1278.4  745.78  1307.6  749.63  1453.6  747.14  1531.7  757.55  1590.3  779.24
  1775.8  824.56  1834.3  836.22  1873.4  840.12  1990.5  836.96  2127.1  810.18
#Mann= 3 , 0 , 0
       0     .07       0    1243    .045       0  1278.4     .08       0
Bank Sta=1243,1278.4
XS Rating Curve= 0 ,0
Exp/Cntr=0.3,0.1

Type RM Length L Ch R = 1 ,59710.8 ,1560.2,1569.5,1578.4
XS GIS Cut Line= 4
     1526630.264      235848.498     1526803.875      236625.408
     1527415.854      236994.332     1527793.459      237424.019
#Sta/Elev= 30
       0  903.48      59  885.12   186.7  858.39   471.8  818.91   540.5     818
     629  811.39     688   813.3   796.1  797.97   815.6  789.66   825.4  782.89
   864.6  747.19   874.4  743.28   884.2  743.71   903.8   747.2   923.3  748.26
  1001.6  746.31  1158.3  748.92  1334.4  744.15  1422.6     746  1442.1  748.21
  1481.3   756.1  1520.4  760.67  1578.5  783.75  1694.9  816.01    1724  822.14
  1820.9  828.75  1840.3  828.38    1976  803.53  1995.4  801.68  2082.7  817.01
#Mann= 3 , 0 , 0
       0      .1       0   864.6    .045       0   884.2    .055       0
Bank Sta=864.6,884.2
XS Rating Curve= 0 ,0
Exp/Cntr=0.3,0.1

Type RM Length L Ch R = 1 ,58141.3 ,2016.6,2036.9,2049.9
XS GIS Cut Line= 4
     1526361.265      235950.186     1526780.217      237040.074
     1527327.092      237712.817     1527930.391      238481.046
#Sta/Elev= 30
       0  906.12    88.3  877.72   186.4  859.41   284.6  846.55   323.8   833.3
   421.9  824.69   529.8  809.87   569.1  811.12     677   824.2   922.3  816.84
  1206.6  818.75  1284.5  813.22  1352.7  802.99  1469.6  781.86  1518.3  769.71
  1683.9  773.39  1937.2  770.53  2024.9  766.73  2093.2  747.61  2259.3  743.05
 2311.89735.8857  2317.9  734.87 2333.65737.9393    2357   746.9    2396  754.94
    2484   821.2  2591.4  869.62  2708.6   898.1  2845.4  910.87  3011.4  937.56
#Mann= 3 , 0 , 0
       0     .05       0 2311.89    .045       0 2333.65     .06       0
Bank Sta=2311.89,2333.65
XS Rating Curve= 0 ,0
Exp/Cntr=0.3,0.1

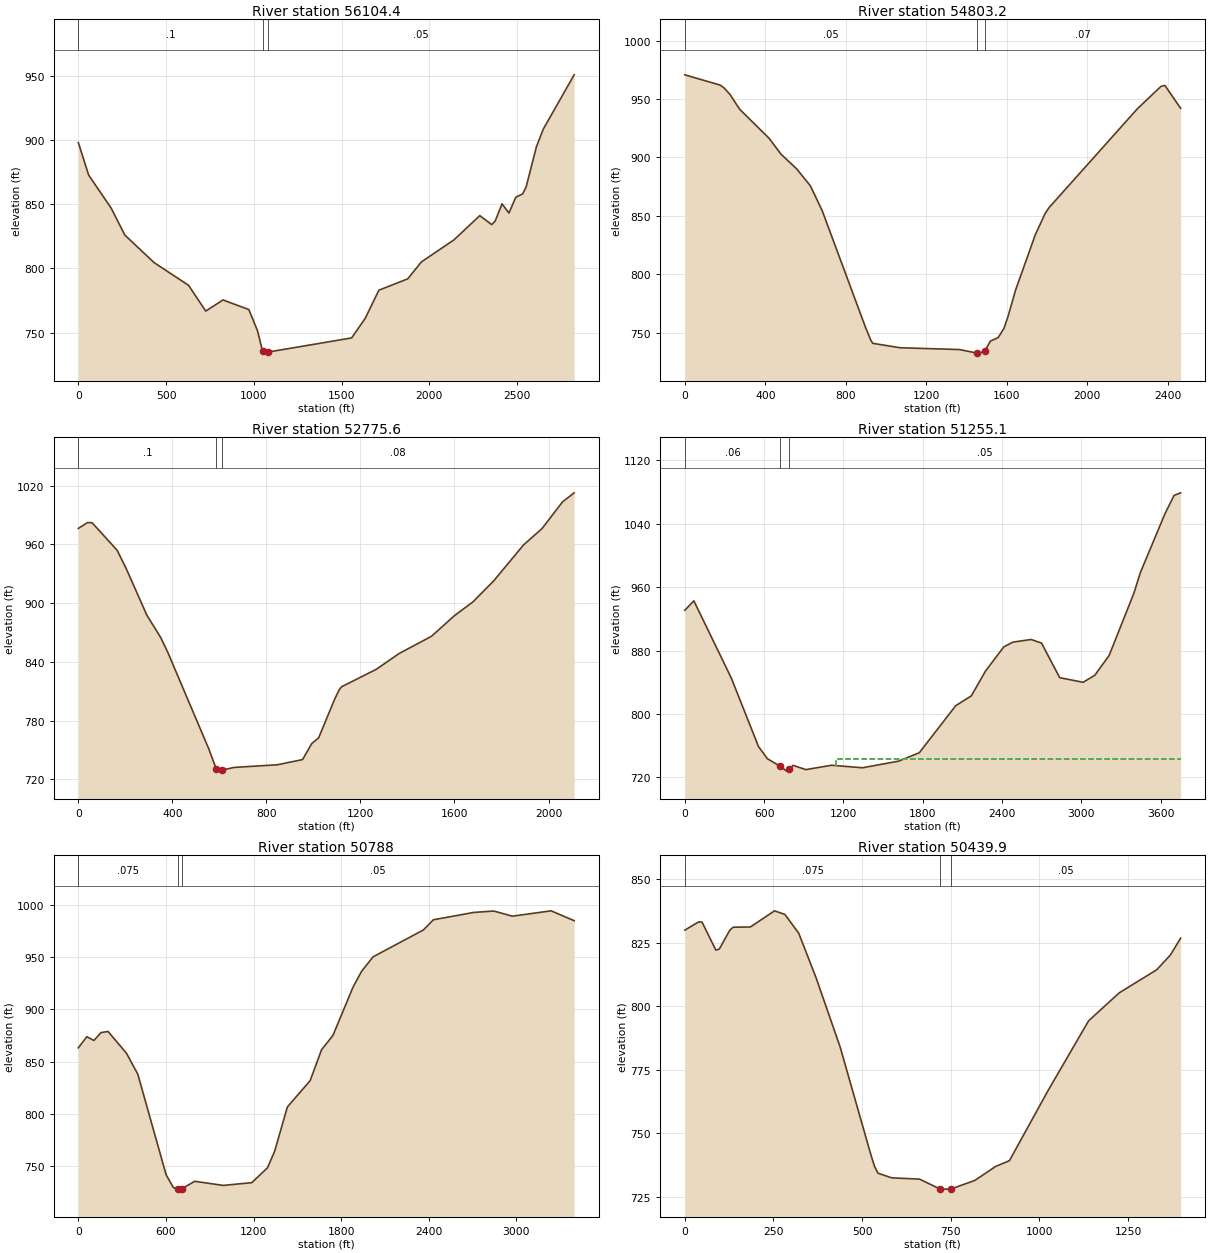
Type RM Length L Ch R = 1 ,56104.4 ,1297.6,1301.1,1300.7
XS GIS Cut Line= 5
      1526198.62      235959.344     1526081.433      236705.872
     1526011.988      237261.428     1526081.433      237877.747
     1526437.335      238693.719
#Sta/Elev= 30
       0  897.87    58.9  872.58   186.5  847.04     265  825.92   431.8  804.49
   628.1  786.82   726.2  766.75   824.4  775.44   971.8  767.94  1020.9   751.6
  1050.3  735.42  1060.2  734.04  1079.8  734.83  1557.8  745.87  1635.4  761.18
  1712.9     783  1877.6  791.85  1955.3  805.02  2141.2   822.2  2287.9  841.03
  2356.4  834.05    2376  836.86  2415.1  850.22  2454.2  843.05  2493.4  855.36
  2532.5  857.98  2552.1  863.25  2610.8  894.58  2649.9  908.33    2826   950.6
#Mann= 3 , 0 , 0
       0      .1       0  1050.3    .045       0  1079.8     .05       0
Bank Sta=1050.3,1079.8
XS Rating Curve= 0 ,0
Exp/Cntr=0.3,0.1

Type RM Length L Ch R = 1 ,54803.2 ,2027.1,2027.6,2025.3
XS GIS Cut Line= 6
     1525215.113      236376.011     1525303.655      237053.094
      1525256.78      237417.678     1525215.113      237730.178
     1525168.238      237974.969     1524939.071      238792.678
#Sta/Elev= 30
       0  970.67   175.6  961.91   195.1  959.48   224.4  953.94   273.1  941.12
   419.5   916.3     478  902.81     556  890.24   624.3  875.68   682.8   854.5
   895.7  755.81   924.7  743.53   934.4  740.99  1069.5  737.22  1365.7  735.66
    1452  732.62  1461.6  732.61  1490.3  734.28  1519.1  742.91  1557.4  745.89
  1586.2  753.76  1605.4  763.44  1644.2  786.65  1741.8  833.77  1790.6  851.95
  1810.2  857.06  2249.4  941.67  2366.5  960.77  2386.1  961.62  2464.2  942.05
#Mann= 3 , 0 , 0
       0     .05       0    1452    .045       0  1490.3     .07       0
Bank Sta=1452,1490.3
XS Rating Curve= 0 ,0
Exp/Cntr=0.3,0.1

Type RM Length L Ch R = 1 ,52775.6 ,1518.1,1520.5,1519.1
XS GIS Cut Line= 4
     1523996.363      236216.289      1523952.96      236641.636
     1523892.196      237006.219     1523840.113      238316.983
#Sta/Elev= 30
       0  976.41    38.9  982.32    58.3  982.28   165.2  954.05   204.1  935.09
   291.5  887.74   349.8  865.11     379  850.65     554  751.66  586.75730.5943
   592.9  728.37   612.4  729.42     661  732.11   846.1  734.86   953.8  740.15
     993  756.61  1022.3  762.42  1090.8  802.18  1110.4  811.83  1120.2  814.65
  1267.1  832.39    1365  848.63    1502  866.15  1599.9  887.28  1678.2  901.29
  1766.3  922.67  1893.6   959.5  1971.9  976.14    2060 1003.65    2109 1012.78
#Mann= 3 , 0 , 0
       0      .1       0  586.75    .045       0   612.4     .08       0
Bank Sta=586.75,612.4
XS Rating Curve= 0 ,0
Exp/Cntr=0.3,0.1

Type RM Length L Ch R = 1 ,51255.1 ,458.6,467.1,471.3
XS GIS Cut Line= 5
     1522737.683      236242.331      1522538.03      236763.164
     1522459.905      237162.469     1522494.627      237735.386
     1522477.266      239948.928
#Sta/Elev= 30
       0  930.76    68.5   942.7   352.3  845.23   557.8  758.97   625.6  743.62
   722.5  734.06   770.9  728.02   790.3  730.47   819.4   735.3   916.2  729.93
  1110.6  735.42  1344.1  732.25  1617.3  740.56  1774.8  751.22  2050.2  810.49
  2168.3  822.88  2276.5  854.38  2414.2  884.65  2483.1  890.62  2620.8  893.93
  2699.6  889.42  2837.3  845.81  3014.4  839.98  3102.9  848.89  3211.1  873.79
  3398.1  952.07  3447.3  978.18  3634.2 1052.66    3703 1075.59  3752.2 1078.82
#Mann= 3 , 0 , 0
       0     .06       0   722.5    .045       0   790.3     .05       0
#XS Ineff= 2 , 0
                         1147.16          743.56
Permanent Ineff=
       F       F
Bank Sta=722.5,790.3
XS Rating Curve= 0 ,0
Exp/Cntr=0.3,0.1

Type RM Length L Ch R = 1 ,50788   ,344.4,348.2,350.3
XS GIS Cut Line= 5
     1522445.206      236097.597     1522192.544      236632.522
     1522041.502      236929.397     1521708.169       237762.73
     1520951.224      239142.938
#Sta/Elev= 30
       0  863.17    58.2   873.8   106.7  870.22   155.2  877.74   203.7  878.85
   329.7  858.04   407.3  838.04   601.4  741.72   650.4  729.62   679.8     728
   709.2  728.39   797.3   735.5     993  731.55  1188.1   734.2  1295.4  748.34
  1344.2  763.96    1432   806.6  1588.1  831.82  1666.1  861.37  1744.2  875.04
  1881.2  921.11  1940.3  936.38    2019  950.24  2363.3  975.91  2432.2  985.68
  2707.7   992.7  2845.4  994.06  2973.3  989.14  3238.9  994.25  3396.4  984.82
#Mann= 3 , 0 , 0
       0    .075       0   679.8    .045       0   709.2     .05       0
Bank Sta=679.8,709.2
XS Rating Curve= 0 ,0
Exp/Cntr=0.3,0.1

Type RM Length L Ch R = 1 ,50439.9 ,144.8,154.8,90.3
XS GIS Cut Line= 5
      1522317.11      236063.945     1521870.061      236552.226
     1521794.106      236665.074     1521651.715      236852.181
     1521510.485      237189.017
#Sta/Elev= 30
       0  829.88    38.9  833.14    48.7  833.04    87.6  822.03    97.4  822.46
   126.6  829.81   136.3  831.04     185  831.14   253.1  837.49   282.3  836.07
   321.3  828.69     370  811.27   438.1  783.94   525.7   741.1   535.5   736.8
   545.2  734.24   584.1  732.43     662  731.94   720.3  728.02     730     728
   749.5     728   817.6  731.39   876.4   736.9   915.6   739.2  1023.4   766.5
  1138.9  794.23  1225.4  805.24  1331.1  814.31  1369.6  820.12  1398.4  826.73
#Mann= 3 , 0 , 0
       0    .075       0   720.3    .045       0   749.5     .05       0
Bank Sta=720.3,749.5
XS Rating Curve= 0 ,0
Exp/Cntr=0.3,0.1

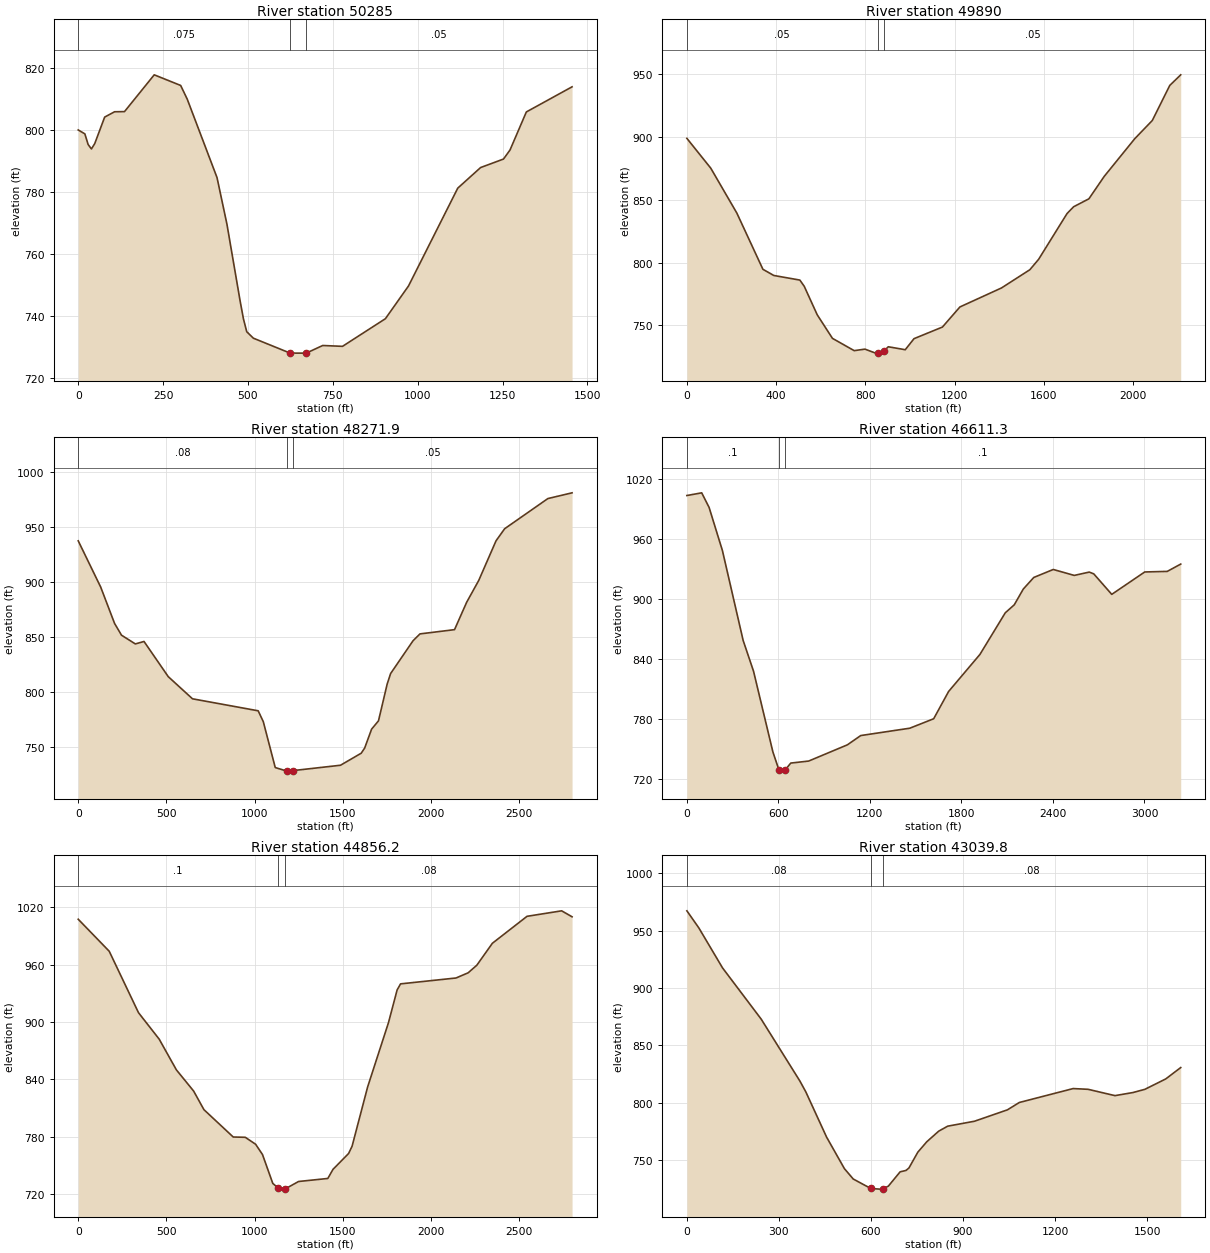
Type RM Length L Ch R = 1 ,50285   ,397.5,395.1,452.4
XS GIS Cut Line= 5
     1522234.644      236028.528     1521787.596       236516.81
     1521711.641      236629.657     1521564.377      236823.168
     1521392.429      237199.434
#Sta/Elev= 30
       0  800.02    19.5  798.76    29.2  795.32    38.9  793.89    48.7  795.63
    77.9  804.17   107.1  805.89   136.3  805.94   223.9  817.81   301.8  814.38
   321.3  809.92   408.9  784.65   438.1  769.62     477   744.8   486.8  739.02
   496.5   734.9     516  732.82   623.1  728.06   641.9     728   671.7     728
   720.3  730.46   778.6  730.19     905  739.11   973.1  749.68  1118.2  781.25
  1185.5  787.89  1252.9  790.63  1272.1  793.55  1320.2  805.83  1454.9  813.94
#Mann= 3 , 0 , 0
       0    .075       0   623.1    .045       0   671.7     .05       0
Bank Sta=623.1,671.7
XS Rating Curve= 0 ,0
Exp/Cntr=0.3,0.1

Type RM Length L Ch R = 1 ,49890   ,1606.5,1618.1,1625.7
XS GIS Cut Line= 4
     1522027.353      235571.671     1521600.269      236234.865
      1521523.88       236398.06     1520812.075      237418.893
#Sta/Elev= 30
       0  898.88   107.1  875.14     224   839.4   340.8  794.69   389.5  789.79
   506.4  786.12   525.9  781.21   584.3  758.47   652.5  739.74   749.9  729.98
   798.3  731.17   845.7     728   855.2     728   883.6  729.64   902.6  733.06
   978.8  730.72    1018   739.5  1145.4  748.75  1223.8  764.74    1410  779.84
  1537.4  794.37  1576.6  802.65  1703.9  839.03  1733.3  844.44  1801.9  850.77
  1870.5   868.6  2007.7  898.65  2086.1  913.09  2164.5  941.02  2213.5  949.43
#Mann= 3 , 0 , 0
       0     .05       0   855.2    .045       0   883.6     .05       0
Bank Sta=855.2,883.6
XS Rating Curve= 0 ,0
Exp/Cntr=0.3,0.1

Type RM Length L Ch R = 1 ,48271.9 ,1661.6,1660.6,1654.4
XS GIS Cut Line= 4
      1521287.22      234864.958     1520502.497      235455.236
     1520252.497      235698.291      1519537.22      236983.013
#Sta/Elev= 30
       0  937.26   127.6  895.17   206.2  862.18   245.5  851.52     324  843.58
   373.1  845.82   510.6  813.85   648.1  793.71  1020.7  782.82  1049.7  772.93
  1117.5  731.25 1182.54 728.056  1191.5     728 1216.41728.4483  1487.5  733.34
  1605.1  744.28  1624.7  748.98  1663.9  766.11  1703.1  773.72  1752.1     807
  1771.8  816.65  1899.2   846.5  1938.4  852.69  2134.4  856.56  2203.1  881.41
  2271.7  901.28  2369.7  937.26  2418.7  948.26  2663.8  975.66    2801  980.88
#Mann= 3 , 0 , 0
       0     .08       0 1182.54    .045       0 1216.41     .05       0
Bank Sta=1182.54,1216.41
XS Rating Curve= 0 ,0
Exp/Cntr=0.3,0.1

Type RM Length L Ch R = 1 ,46611.3 ,1754.7,1755,1751.9
XS GIS Cut Line= 6
     1520856.664      233844.125     1520592.775      234239.958
     1520384.442      234559.402     1520064.997      234989.958
     1519714.396      235589.242     1519343.036      236677.964
#Sta/Elev= 30
       0 1003.64    97.1 1006.34   145.6  991.76     233  948.56   368.9  858.69
   436.9  827.97   563.7  747.29   602.9   729.5   622.4     728     642  728.78
   681.1  736.05   798.4  738.07  1052.1  754.28  1139.8  763.57  1461.7  770.93
  1618.1  780.38  1715.9  807.65  1921.3  844.71  2087.5  886.34  2146.5  894.35
  2205.5  910.08  2274.3  921.69  2402.2  929.68  2539.8  923.74  2638.1  927.07
  2667.6   925.3  2785.6  904.78  3001.9  927.19  3149.4  927.76  3237.8  935.06
#Mann= 3 , 0 , 0
       0      .1       0   602.9    .045       0     642      .1       0
Bank Sta=602.9,642
XS Rating Curve= 0 ,0
Exp/Cntr=0.3,0.1

Type RM Length L Ch R = 1 ,44856.2 ,1811.8,1816.5,1818
XS GIS Cut Line= 4
     1519736.757      234031.625     1519262.798      234974.333
     1519111.757      235224.333      1518507.59       236547.25
#Sta/Elev= 30
       0 1007.65   175.9  974.13     342  909.81   459.2  882.15   556.9  849.96
   654.6  827.81   713.2  808.29   879.3  779.68   947.7  779.37  1006.3   772.1
  1045.4  761.32  1103.8  731.08    1133  726.49    1172  725.11  1249.9  733.09
    1416  736.28  1445.5  745.84  1533.9  762.42  1553.6  770.01    1642  832.19
    1760  899.34  1809.1  933.63  1828.7     940  2143.2  946.15    2212  951.57
  2261.1  959.48  2349.6  982.51  2546.1 1010.72  2742.6 1016.47  2801.6 1010.22
#Mann= 3 , 0 , 0
       0      .1       0    1133    .045       0    1172     .08       0
Bank Sta=1133,1172
XS Rating Curve= 0 ,0
Exp/Cntr=0.3,0.1

Type RM Length L Ch R = 1 ,43039.8 ,262.3,263.7,265
XS GIS Cut Line= 4
     1518419.048      233432.666     1518028.423         233766.
      1517882.59      233943.083     1517580.507      234755.583
#Sta/Elev= 30
       0  967.28    38.8  952.44   116.3  917.46   242.2  872.81   368.2  818.87
   387.6   809.4   455.4  769.88   513.5  742.37   542.2  733.34   599.5  725.06
   628.2   724.5   637.8  724.54   656.9  727.16   695.1  739.58   714.2  740.79
   723.8  742.94   752.7  756.69   781.9  765.79   820.8  775.05   850.1  779.41
   937.7  783.74  1044.8  793.66  1083.8  800.09  1259.1  812.22  1307.8  811.58
  1395.5  806.06  1453.9  808.75  1492.9  811.55  1561.1  820.66  1609.8  830.55
#Mann= 3 , 0 , 0
       0     .08       0   599.5    .045       0   637.8     .08       0
Bank Sta=599.5,637.8
XS Rating Curve= 0 ,0
Exp/Cntr=0.3,0.1

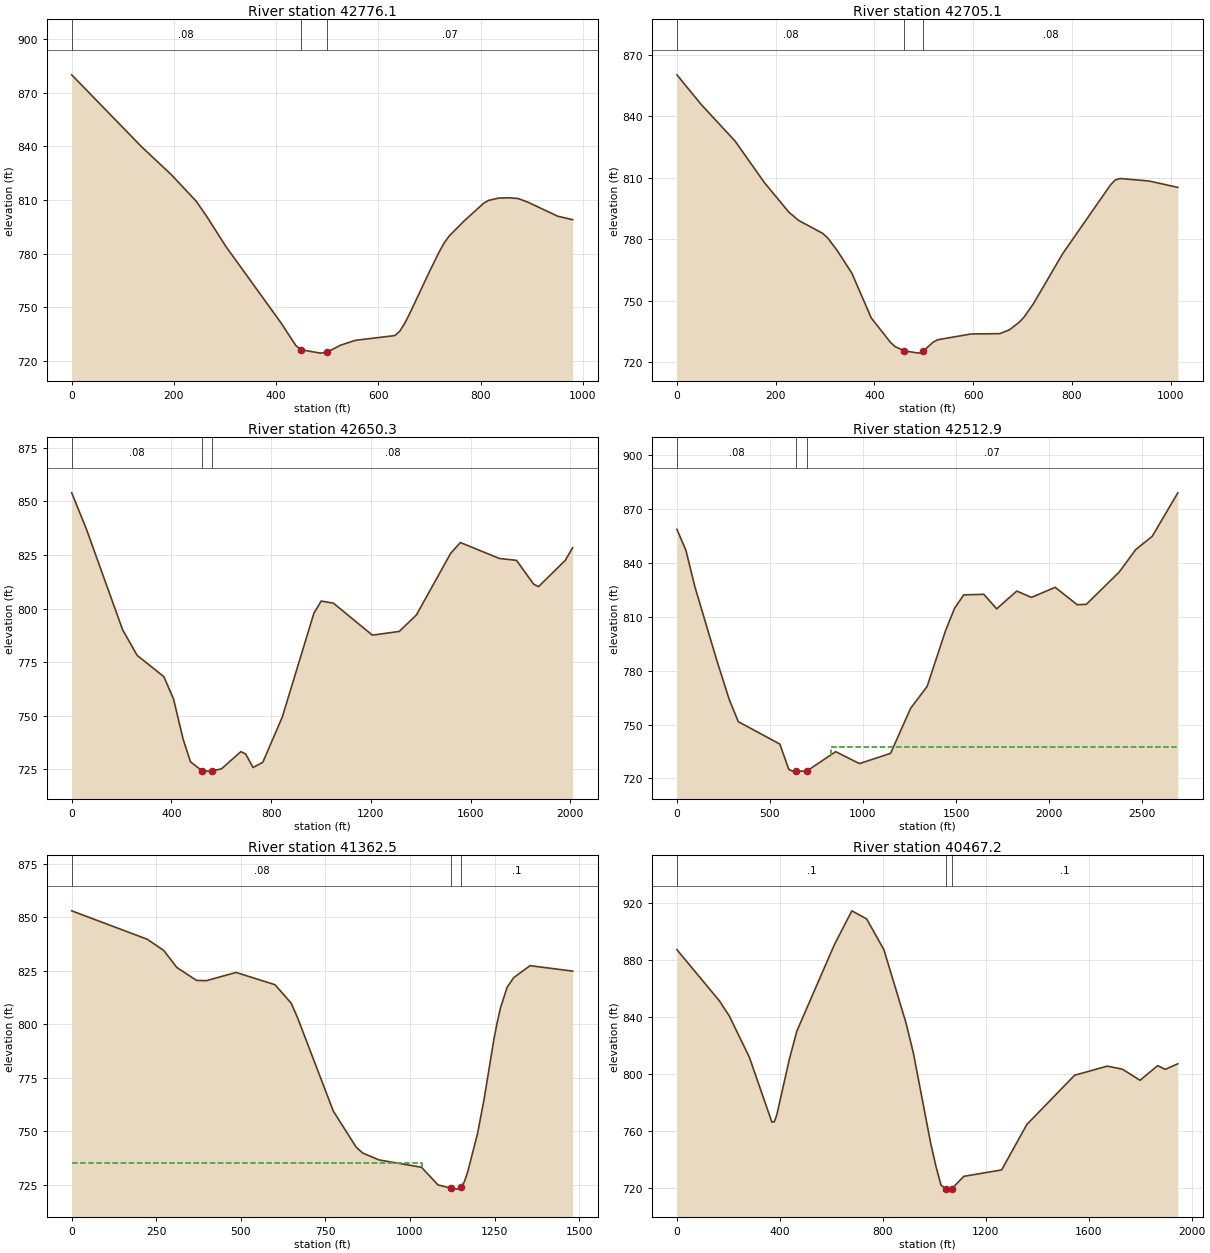
Type RM Length L Ch R = 1 ,42776.1 ,71.2,71,70.6
XS GIS Cut Line= 4
     1518145.611      233316.781     1517843.527      233592.822
     1517744.569      233699.593     1517549.257      234077.197
#Sta/Elev= 30
       0  879.92   136.4  839.83   194.9  824.16   243.6  809.32   263.1   801.3
     302   783.9   409.2  741.51   438.3  728.81     448  726.44   486.8  724.51
  499.58725.0732   525.7  728.91   554.8  731.65   632.1  734.31   641.8  736.77
   651.4  741.15   661.1  746.57   699.7  769.95     719  781.12   728.7  786.08
   738.4  789.92   767.4  798.27     806  808.24   815.7  809.82     835  811.09
   854.3  811.28   873.6  810.84     893  808.72   950.9  800.94   979.9  799.03
#Mann= 3 , 0 , 0
       0     .08       0     448    .045       0  499.58     .07       0
Bank Sta=448,499.58
XS Rating Curve= 0 ,0
Exp/Cntr=0.3,0.1

Type RM Length L Ch R = 1 ,42705.1 ,56.6,54.8,52.8
XS GIS Cut Line= 4
     1518088.319      233259.489     1517796.652      233538.135
      1517695.09      233652.718     1517460.715      234045.947
#Sta/Elev= 30
       0  860.32    49.2  845.83   118.1  827.84   177.1  807.66   226.3  793.29
     246  789.22   295.2  782.82     305  780.68   324.7  774.41   354.2  763.38
   393.5   741.5   432.1  729.65   441.7  727.45   460.8  725.39   489.5  724.28
   499.1  725.27   518.2  729.55   527.8   730.8   595.4  733.64   653.9  733.81
   673.4  735.69   692.8  739.32   702.6  741.78   722.1   748.5   780.5  772.66
   877.9  806.49   887.6  808.92   897.4  809.64   955.8  808.42  1014.3  805.31
#Mann= 3 , 0 , 0
       0     .08       0   460.8    .045       0   499.1     .08       0
Bank Sta=460.8,499.1
XS Rating Curve= 0 ,0
Exp/Cntr=0.3,0.1

Type RM Length L Ch R = 1 ,42650.3 ,131.2,137.4,142.7
XS GIS Cut Line= 6
     1518072.694       233178.76     1517731.548      233525.114
     1517627.382      233663.135     1517247.173      234056.364
     1517191.512      234275.125     1517172.377      234852.357
#Sta/Elev= 30
       0  854.02    58.3  837.29   204.2  790.09   262.5  778.14   369.5  768.21
   408.4  757.78   447.3  738.87   476.4  728.45   524.6   724.1     563   724.1
   601.4  725.23   678.6  733.21   698.1  732.06   727.4  725.79   766.5  728.23
   844.6  749.33   971.6  797.85  1000.9   803.5  1049.8  802.51    1206  787.58
    1314  789.32  1382.7  797.01  1519.9  825.75    1559  830.82  1715.7  823.37
  1784.2   822.5  1852.7  811.42  1872.3  810.21    1980  822.53  2009.3   828.4
#Mann= 3 , 0 , 0
       0     .08       0   524.6    .045       0     563     .08       0
Bank Sta=524.6,563
XS Rating Curve= 0 ,0
Exp/Cntr=0.3,0.1

Type RM Length L Ch R = 1 ,42512.9 ,1134.7,1150.3,1164.9
XS GIS Cut Line= 5
     1518087.451      233020.774     1517660.368      233430.496
     1517524.951      233538.135      1516663.84      233899.246
     1516000.502      234638.815
#Sta/Elev= 30
       0  858.77    48.5  847.08      97  826.68   213.4  786.12   281.4  763.95
   329.9  751.65     553  739.17   601.4  725.09   620.7   724.1   639.9   724.1
   697.6   724.1   853.3  734.94   981.1  728.29  1148.2     734  1256.3  759.12
  1344.7  771.27    1443  802.15  1492.2   814.8  1541.3  822.28  1649.4   822.6
  1718.3   814.5  1826.5  824.41  1905.2  820.86    2033  826.49  2151.1  816.81
  2200.2  817.01  2377.3  835.03  2465.8   847.5  2554.4   854.9    2692  879.12
#Mann= 3 , 0 , 0
       0     .08       0   639.9    .045       0   697.6     .07       0
#XS Ineff= 2 , 0
                          827.76          737.74
Permanent Ineff=
       F       F
Bank Sta=639.9,697.6
XS Rating Curve= 0 ,0
Exp/Cntr=0.3,0.1

Type RM Length L Ch R = 1 ,41362.5 ,894.8,895.4,893.2
XS GIS Cut Line= 6
     1518499.777      232896.642     1518035.961      232673.207
     1517807.069      232552.892     1517572.694        232495.6
     1517348.736        232495.6     1517129.986      232599.767
#Sta/Elev= 30
       0  852.94   223.4  839.67     272  834.46   310.8   826.5   369.1  820.46
   398.3  820.35   485.7  824.18     601  818.47   648.9  809.84   668.1   802.9
   773.4  759.46     841  742.63   860.3   739.9   908.5  736.68  1034.2  733.25
  1082.8  725.02  1121.8  723.46  1141.3  723.05  1151.5  723.96  1160.8  726.47
  1170.5  730.99  1199.7  748.92  1219.2  765.05  1248.3  793.14    1258   800.9
  1267.7   807.7  1287.1  817.21  1306.5  821.74    1355  827.34  1480.9  824.81
#Mann= 3 , 0 , 0
       0     .08       0  1121.8    .045       0  1151.5      .1       0
#XS Ineff= 2 , 0
         1034.57  735.22
Permanent Ineff=
       F       F
Bank Sta=1121.8,1151.5
XS Rating Curve= 0 ,0
Exp/Cntr=0.3,0.1

Type RM Length L Ch R = 1 ,40467.2 ,823.1,787.4,750.9
XS GIS Cut Line= 6
     1519010.194      232297.684     1518426.861      231948.725
     1518140.402      231927.892     1517885.194      231943.517
     1517631.426      232090.227     1517327.381      232394.828
#Sta/Elev= 30
       0  887.49   165.1  851.57   203.9  840.84   281.6   811.9     369  766.39
   378.7  766.68   388.4  771.72     437  810.62   466.1  830.35   611.8  891.01
   679.7  914.79   737.2   909.1   804.2   887.5   890.4  835.88   919.1  814.56
   986.6  750.95  1006.3  735.43    1026  722.15  1045.6   719.3  1067.8719.5066
  1114.5  728.28  1261.7  732.79  1359.4  764.66  1545.1  799.28  1672.3  805.71
    1731  803.54  1799.4  795.75  1867.9  806.06  1897.2  803.42  1946.2  807.35
#Mann= 3 , 0 , 0
       0      .1       0  1045.6    .045       0  1067.8      .1       0
Bank Sta=1045.6,1067.8
XS Rating Curve= 0 ,0
Exp/Cntr=0.3,0.1

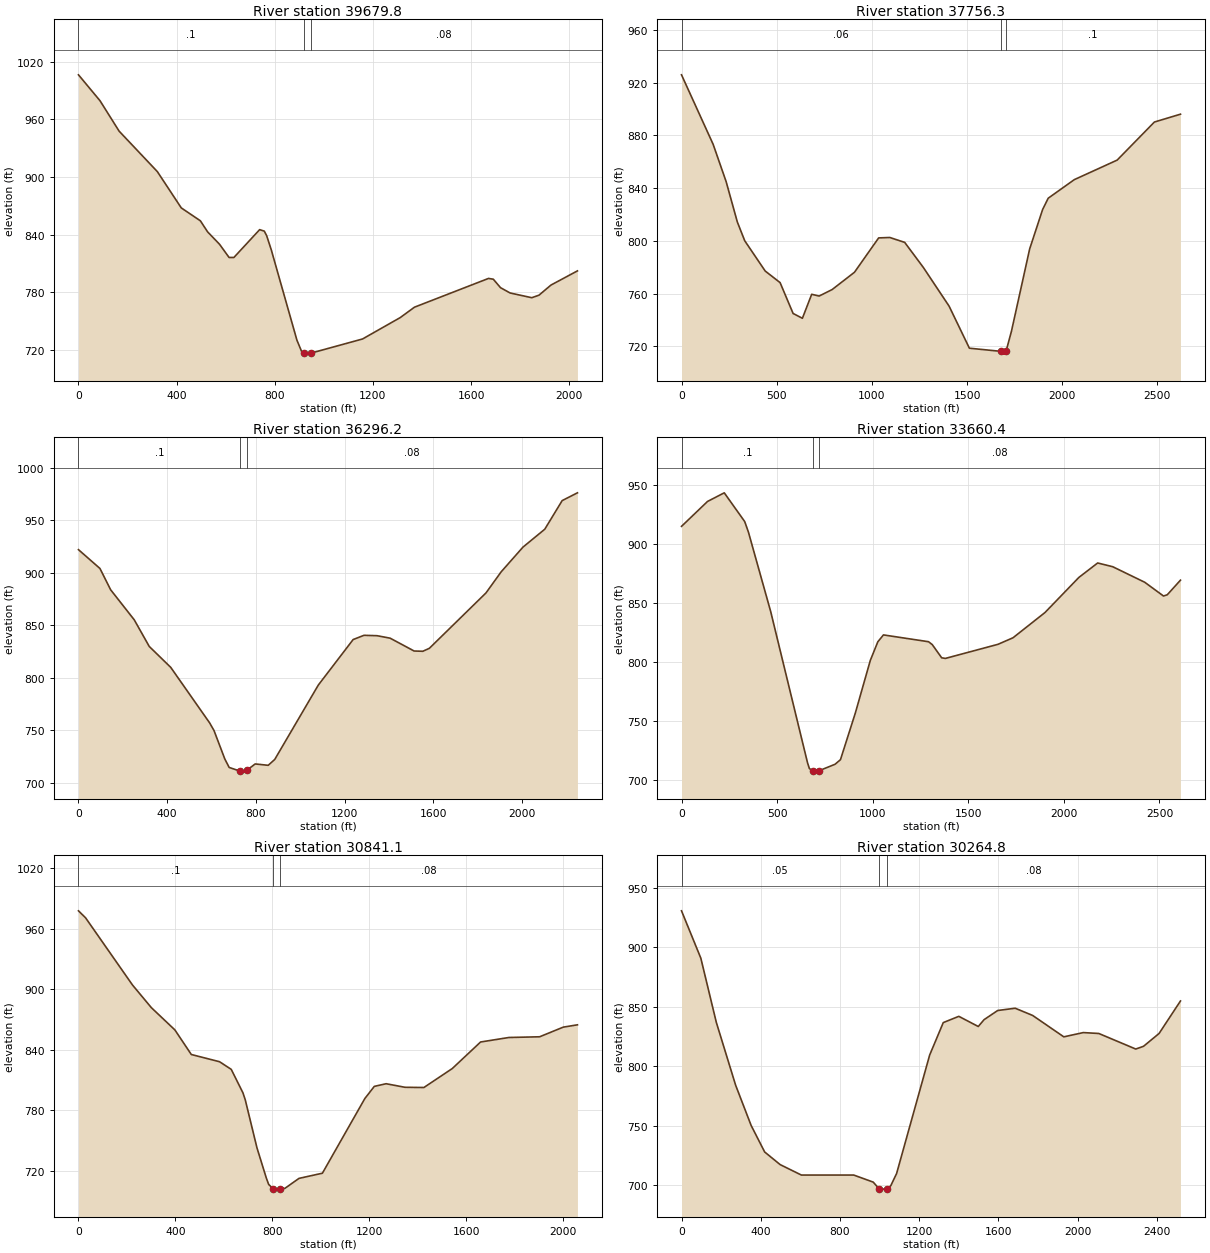
Type RM Length L Ch R = 1 ,39679.8 ,1913.3,1923.5,1931.8
XS GIS Cut Line= 6
     1517968.527      230604.975     1517572.694      231136.225
     1517520.611      231318.517     1517593.527      231917.475
     1517522.693      232099.689     1517286.582      232400.037
#Sta/Elev= 30
       0 1006.48    87.7  979.54   165.6  947.86   321.5  905.71   418.9  867.98
   496.9  854.52   526.1  843.08   574.8  830.14   613.8  816.36   633.3  816.33
   738.3  845.33   757.3  843.79   766.8  839.15   785.7  824.38   890.3  730.29
   909.4  718.51   918.9     717   928.5   716.8   947.6   716.8  1157.8  731.53
  1311.7  753.84  1369.4  764.62  1671.1  794.55  1690.7  793.74  1720.1  784.92
  1759.3  779.39  1847.4  774.49  1876.8   777.1  1925.8  787.66  2033.6   802.4
#Mann= 3 , 0 , 0
       0      .1       0   918.9    .045       0   947.6     .08       0
Bank Sta=918.9,947.6
XS Rating Curve= 0 ,0
Exp/Cntr=0.3,0.1

Type RM Length L Ch R = 1 ,37756.3 ,1446.4,1460.1,1471.9
XS GIS Cut Line= 5
     1516984.152        230745.6     1516577.902      231969.559
     1516473.736      232261.225     1516390.402        232495.6
     1516333.111      233266.434
#Sta/Elev= 30
       0  925.94   166.1  873.24   234.5  844.88   293.1  814.35   332.2  800.03
   439.6   777.1   517.8  768.32   586.2   744.9     635  741.26   683.9  759.46
     723  758.12   791.4  763.06   908.6  776.17  1035.6  802.23  1094.2  802.54
  1172.4  798.83  1270.1  779.86  1405.8  750.42  1512.2  718.56  1675.9  716.19
    1695  714.82  1704.6  716.08  1733.3   731.5  1828.9  793.89    1897  823.81
  1926.4  832.35  2063.3  846.42  2288.4  861.24  2484.1  890.13    2621  896.08
#Mann= 3 , 0 , 0
       0     .06       0  1675.9    .045       0  1704.6      .1       0
Bank Sta=1675.9,1704.6
XS Rating Curve= 0 ,0
Exp/Cntr=0.3,0.1

Type RM Length L Ch R = 1 ,36296.2 ,2636.7,2635.8,2633.2
XS GIS Cut Line= 4
     1516760.194      230604.975     1516411.236      230896.642
     1516093.527      231157.059     1515135.194      232157.059
#Sta/Elev= 30
       0  922.17    96.8  904.24   145.2  883.88   251.6  855.25   319.3  829.86
   416.1  809.94   591.7  756.97   611.3   749.7   660.2  722.51   679.8   714.5
   728.7  711.03   737.6     711     758  711.62   797.1  717.85   855.8  716.55
   885.2  722.11  1081.7  793.02  1238.9  836.45    1288  840.51  1346.9  840.13
  1405.9  837.77  1513.9  825.54  1553.2  825.28  1582.7   828.1  1838.1   880.9
  1906.8  901.07  2005.1  924.61  2103.3  941.65  2181.9  968.97  2250.7  976.37
#Mann= 3 , 0 , 0
       0      .1       0   728.7    .045       0     758     .08       0
Bank Sta=728.7,758
XS Rating Curve= 0 ,0
Exp/Cntr=0.3,0.1

Type RM Length L Ch R = 1 ,33660.4 ,2835.6,2819.3,2794.8
XS GIS Cut Line= 5
     1516472.868       228893.17     1516030.159       229210.01
     1515800.125      229440.045     1515344.395      230242.996
     1514862.625      230902.718
#Sta/Elev= 30
       0  914.83   136.1  935.88   223.6  943.17   330.5  918.88     350  909.97
   466.6  842.71   659.2  714.91   668.8  710.12   687.9   707.9   716.6  708.05
   802.8  713.68   831.4  717.56     909   756.9   987.6  801.51  1026.9  817.24
  1056.3  823.05  1292.1   817.3  1311.7  814.84  1360.8   803.7  1380.5  803.19
  1655.5  815.11  1734.1  820.64  1901.3  841.99  2078.4  871.63  2176.8  883.86
  2255.6   880.7  2422.9  867.57  2521.3  855.92    2541  857.01  2609.9  869.33
#Mann= 3 , 0 , 0
       0      .1       0   687.9    .045       0   716.6     .08       0
Bank Sta=687.9,716.6
XS Rating Curve= 0 ,0
Exp/Cntr=0.3,0.1

Type RM Length L Ch R = 1 ,30841.1 ,562.6,576.2,589.2
XS GIS Cut Line= 4
      1514226.34      229036.399     1514033.544      229626.599
     1514085.627      230038.057     1514523.215      230963.482
#Sta/Elev= 30
       0  977.84    29.1  970.95   223.1  904.18   300.7  881.78   397.8  859.69
   465.7  835.28   582.1  828.12   630.5  820.53   678.8  797.22   688.4  790.24
   736.6  742.69   775.2  712.74   784.9   706.4   804.2  701.84   822.7   701.7
   833.1   701.7   852.4  702.55   910.2  712.37  1006.7   717.5  1181.9   791.6
  1220.9  803.64  1269.6  806.28  1347.6  802.74  1425.6  802.53  1542.6  821.32
  1659.6  847.69  1776.6  852.16  1903.3  852.86  2000.8  862.43  2059.3  864.73
#Mann= 3 , 0 , 0
       0      .1       0   804.2    .045       0   833.1     .08       0
Bank Sta=804.2,833.1
XS Rating Curve= 0 ,0
Exp/Cntr=0.3,0.1

Type RM Length L Ch R = 1 ,30264.8 ,1578.2,1579.8,1577.8
XS GIS Cut Line= 4
     1513898.127      228928.682     1513627.382      229640.566
     1513460.715      229953.066     1512606.548      231067.649
#Sta/Elev= 30
       0  930.48    97.6  890.66   175.8  836.73   273.4  783.89   351.5  750.16
   419.9  727.83     498  717.22   605.4  708.43   869.8  708.43   968.2  702.49
   997.7  696.92  1007.6   696.6  1037.1  696.63  1056.8  699.45  1086.3   709.7
  1253.3  809.27    1322  836.55  1400.6  841.81  1498.8  833.26  1528.2  839.03
    1597  846.72  1685.4  848.62  1773.7  842.53  1930.8  824.58    2029  828.15
  2107.6   827.4  2294.2  814.33  2333.5  816.64    2412  827.41    2520  854.71
#Mann= 3 , 0 , 0
       0     .05       0   997.7    .045       0  1037.1     .08       0
Bank Sta=997.7,1037.1
XS Rating Curve= 0 ,0
Exp/Cntr=0.3,0.1

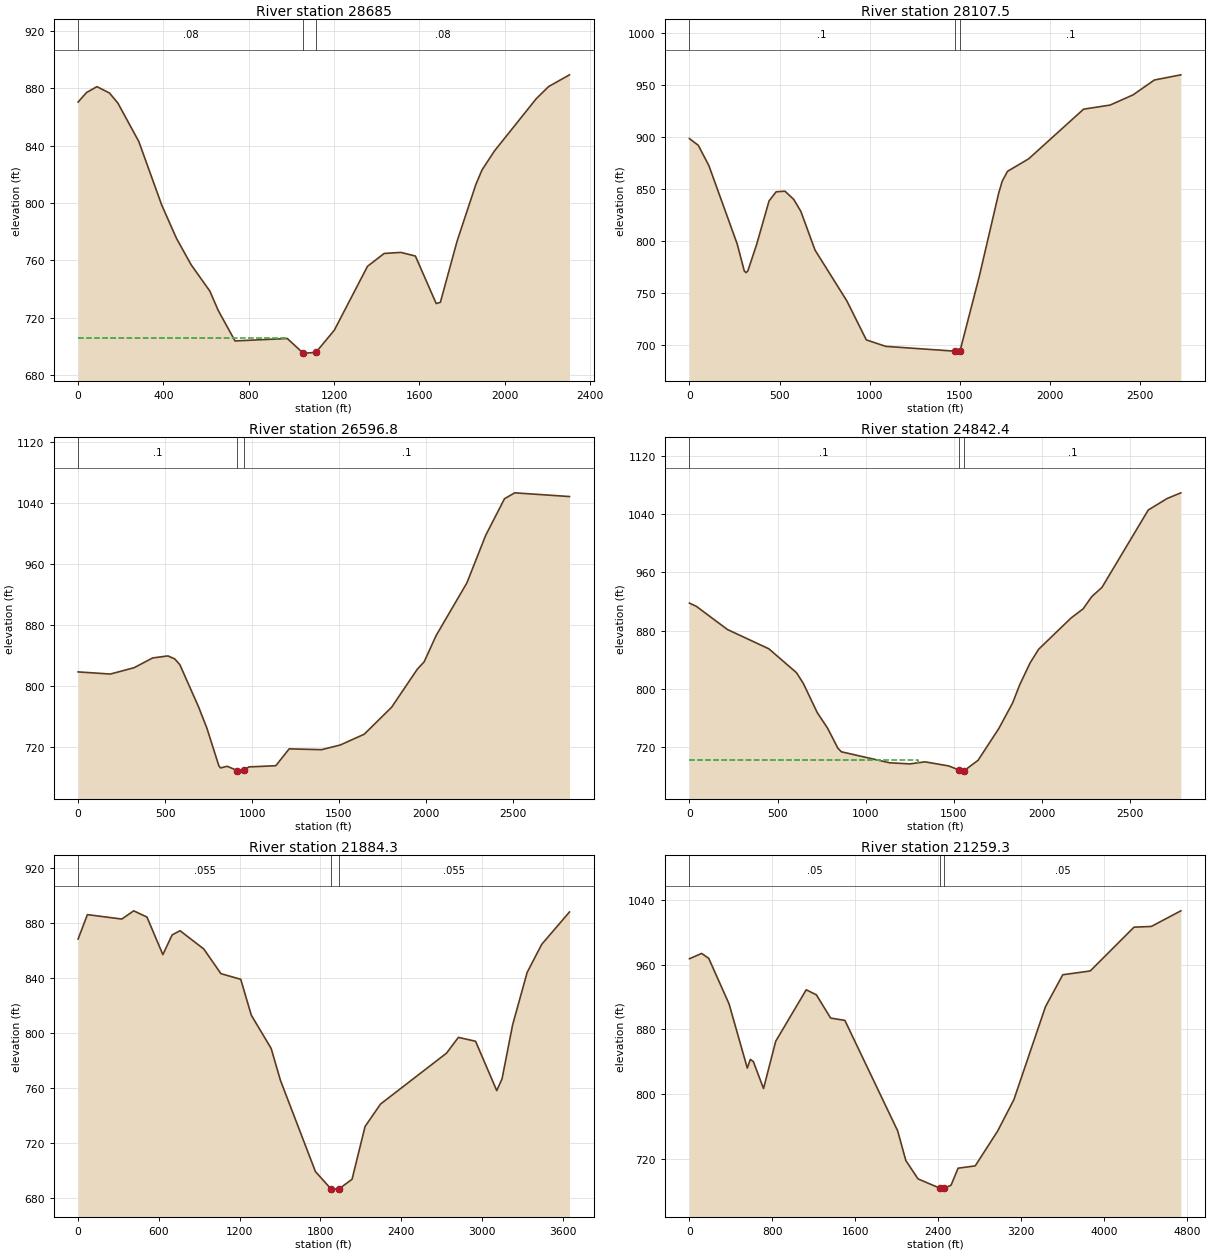
Type RM Length L Ch R = 1 ,28685   ,565,577.5,588.1
XS GIS Cut Line= 4
      1513132.59      228677.024     1512471.132      229400.982
     1512361.757      229635.357     1512028.423      230645.774
#Sta/Elev= 30
       0  870.44    39.2  877.05    88.3   881.2   147.1  876.75   186.3  869.75
   284.4  842.96   392.2  798.49   460.9  775.42   529.5  757.02   617.8   738.5
     657  724.99   735.5  703.81   980.6   705.5  1052.8695.5544  1066.8   695.3
  1114.7  695.84    1201  711.33  1356.4  755.86  1434.5  764.82  1512.6  765.57
  1580.9  763.02  1678.5  729.88    1698  730.74  1776.1  773.28    1864  812.82
  1893.3  823.12  1951.8  836.39  2147.1  872.74  2205.6  881.29  2303.2  889.44
#Mann= 3 , 0 , 0
       0     .08       0  1052.8    .045       0  1114.7     .08       0
#XS Ineff= 2 , 0
          970.58  705.69
Permanent Ineff=
       F       F
Bank Sta=1052.8,1114.7
XS Rating Curve= 0 ,0
Exp/Cntr=0.3,0.1

Type RM Length L Ch R = 1 ,28107.5 ,1503.3,1510.7,1513.4
XS GIS Cut Line= 4
     1513254.898      228213.839     1512210.715      228979.107
     1511856.548      229239.524     1511143.007      229927.024
#Sta/Elev= 30
       0  898.53      49  892.12   107.9  872.51   264.8  797.22     304  771.35
   313.8  769.68   323.6  771.31   372.7  796.86   441.3  838.62   480.6   847.4
   529.6  848.03   578.6  840.01   617.9  828.53   696.3   791.4   872.9   742.5
   980.8  705.04  1088.6   698.8  1470.4  694.22    1490  692.31  1499.7  693.92
  1607.2  766.08  1714.6  845.94  1734.2  857.55  1763.6  867.08  1881.4  879.15
  2185.5  926.85  2332.6  930.78  2460.2  940.61  2577.9  954.88    2725  959.87
#Mann= 3 , 0 , 0
       0      .1       0  1470.4    .045       0  1499.7      .1       0
Bank Sta=1470.4,1499.7
XS Rating Curve= 0 ,0
Exp/Cntr=0.3,0.1

Type RM Length L Ch R = 1 ,26596.8 ,1753.7,1754.5,1750.3
XS GIS Cut Line= 4
     1513033.632      227354.107     1512252.382      227598.899
     1511846.132      227775.982     1510684.673      228822.857
#Sta/Elev= 30
       0  818.85   185.2  816.02   321.6   824.3   428.8  837.13   516.6  839.77
   555.6  835.88   584.8  828.42     692   773.4   740.7   745.1     809  696.12
   818.7   693.1   857.2  695.24     915  689.69   924.7   688.9   953.6  690.38
   982.5  694.44  1136.6  695.97  1213.7  718.06  1399.6  716.99  1507.7  723.14
  1645.4  737.27  1802.8  772.59  1950.3  822.35  1989.6  831.97  2058.4  866.36
  2235.4  935.36  2343.6  997.65  2451.8 1045.65  2510.8 1053.35  2825.5 1048.48
#Mann= 3 , 0 , 0
       0      .1       0     915    .045       0   953.6      .1       0
Bank Sta=915,953.6
XS Rating Curve= 0 ,0
Exp/Cntr=0.3,0.1

Type RM Length L Ch R = 1 ,24842.4 ,2950.6,2958.1,2959.8
XS GIS Cut Line= 5
     1512330.507      226588.482     1511200.298      226713.482
      1510882.59      226781.191     1510481.548      227010.357
     1509736.757      227453.066
#Sta/Elev= 30
       0  917.67    39.2  913.23   215.7   881.4   450.9  854.92   607.8  822.14
     647   807.2   725.4  767.46   784.2  745.99     843  718.41   862.6  713.53
  1137.1  698.42  1251.8   696.9  1337.7  699.72  1471.8  694.14  1530.7  688.53
  1550.4  686.98  1560.2  687.69  1638.8  701.83  1756.8  745.54  1835.4   780.8
  1874.7  805.19  1933.6  835.26  1982.2  854.17  2167.2  897.29  2235.4   909.8
    2284  926.47  2342.5  939.29  2605.3  1045.5  2712.4 1061.27  2790.3 1069.07
#Mann= 3 , 0 , 0
       0      .1       0  1530.7    .045       0  1560.2      .1       0
#XS Ineff= 2 , 0
         1298.89  702.05
Permanent Ineff=
       F       F
Bank Sta=1530.7,1560.2
XS Rating Curve= 0 ,0
Exp/Cntr=0.3,0.1

Type RM Length L Ch R = 1 ,21884.3 ,621.1,625,626.1
XS GIS Cut Line= 6
     1513002.382      225770.774      1512070.09      224885.357
     1511643.007      224552.024     1511419.048      224624.941
     1511241.965      224786.399     1510450.298      225874.941
#Sta/Elev= 30
       0  868.38    68.9   886.1   324.6  882.89   413.1  888.86   511.5  884.32
   629.6  857.06   698.2  871.35     757  874.42   933.5  861.15  1060.9  843.21
    1208  839.13  1286.4  813.06    1434  788.89  1502.8  765.73  1762.9  699.43
  1877.8  686.91  1896.8   686.7  1936.7  686.82  2034.8  693.86  2131.4  732.18
  2246.4  748.51  2736.2  785.45  2824.6  796.94  2952.3  794.11  3109.5  758.28
  3148.8  766.79  3227.4  806.02  3335.5  844.14  3443.6  864.51  3649.9  888.04
#Mann= 3 , 0 , 0
       0    .055       0  1877.8    .045       0  1936.7    .055       0
Bank Sta=1877.8,1936.7
XS Rating Curve= 0 ,0
Exp/Cntr=0.3,0.1

Type RM Length L Ch R = 1 ,21259.3 ,2203.4,2214.7,2216.1
XS GIS Cut Line= 6
     1513528.423      224729.107     1512783.632      224239.524
     1512143.007      224140.566      1511405.45      224036.023
      1511030.45      224124.564     1509309.673      225281.191
#Sta/Elev= 30
       0  967.44   117.5  974.04   186.1  967.93     382  911.65   558.3  832.11
   587.7  842.94     617  840.07     715   806.8   832.5  865.32    1127  929.02
  1225.2  922.77  1362.7  894.01  1500.2  891.16    2010  754.35  2088.4  717.72
    2206     695  2419.3  683.34  2438.6   682.3  2457.8683.2064  2525.3   687.2
  2592.7  708.22  2758.2  711.05  2974.4  754.13  3131.6  793.08  3436.2  908.05
  3603.3  947.62  3868.6  952.34  4291.1 1006.53  4458.2 1007.41  4743.1 1026.75
#Mann= 3 , 0 , 0
       0     .05       0  2419.3    .045       0  2457.8     .05       0
Bank Sta=2419.3,2457.8
XS Rating Curve= 0 ,0
Exp/Cntr=0.3,0.1