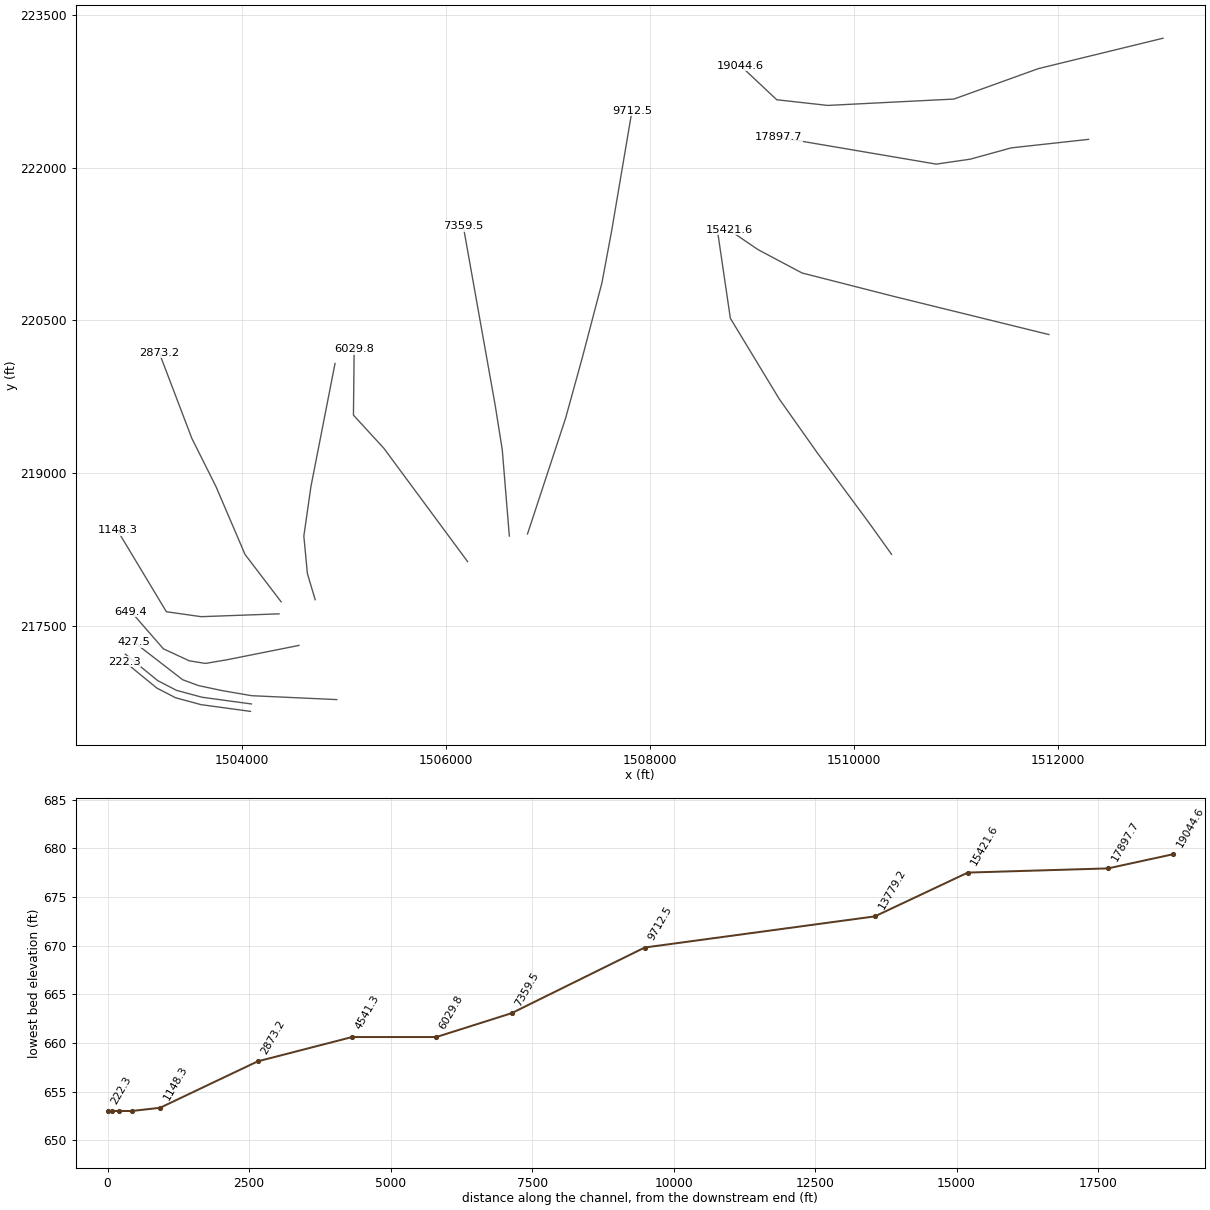
HEC-RAS study INDNCR.prj: INDNCR

--- INDNCR.g01 (geometry) --- (continued)

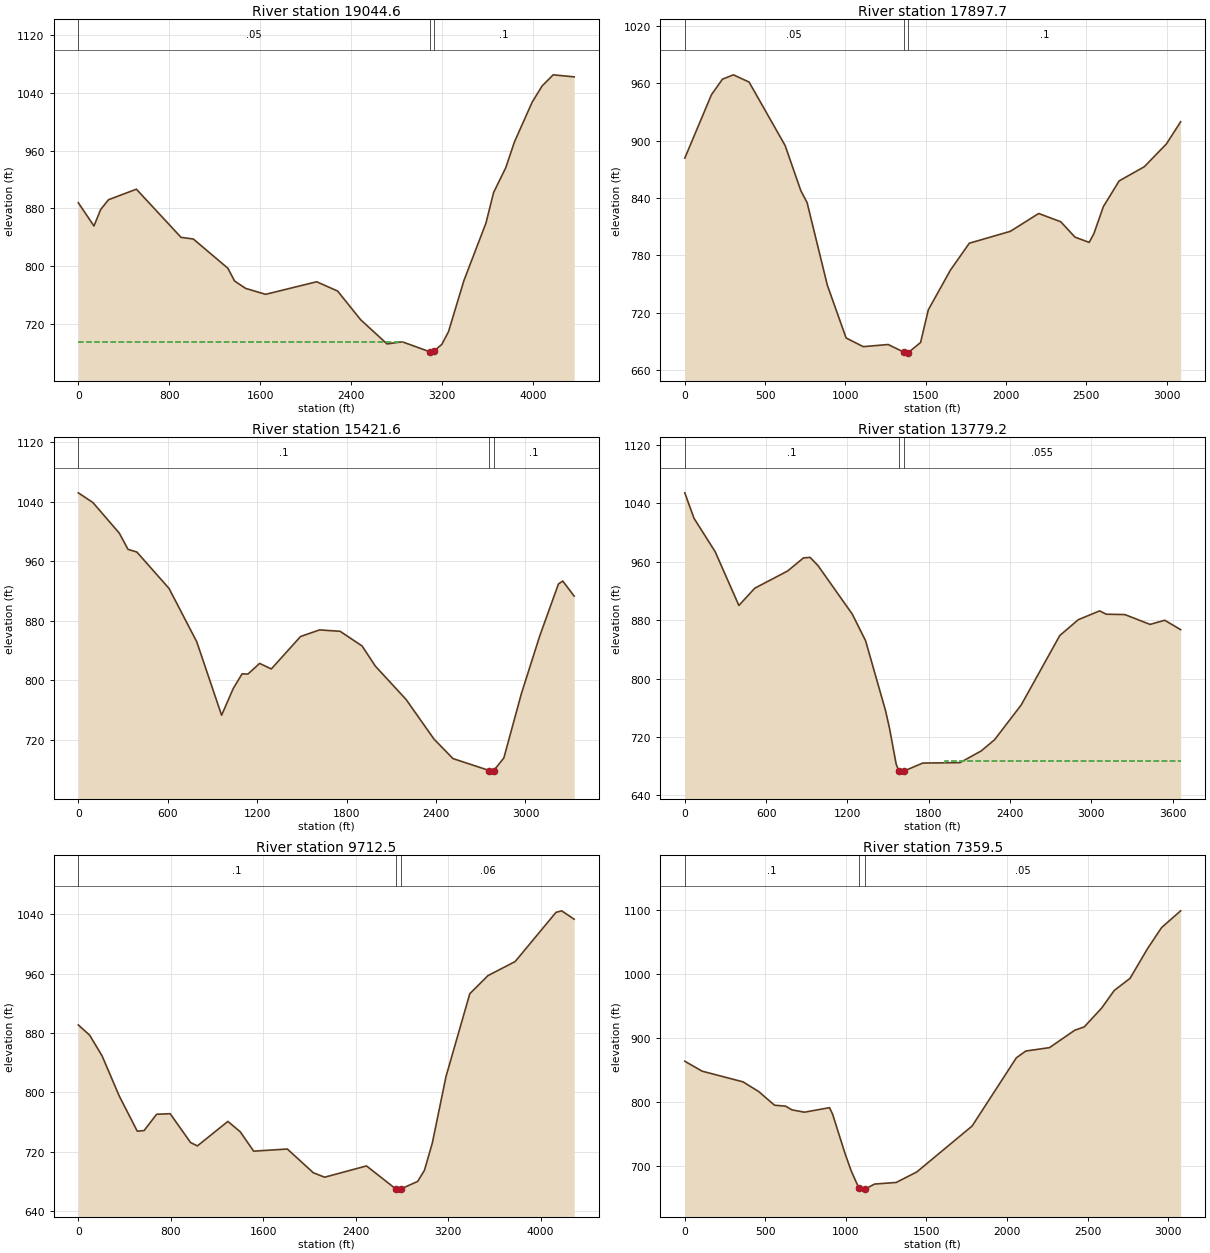
Type RM Length L Ch R = 1 ,19044.6 ,1138.1,1146.9,1144
XS GIS Cut Line= 6
     1513030.159      223270.774     1511807.937      222972.163
     1510981.548      222673.552     1509745.437      222611.052
     1509245.437      222666.607      1508891.27      222999.941
#Sta/Elev= 30
       0  887.84   137.6  855.63   196.6  878.47   265.4  892.02   511.1  906.66
   904.3  839.87  1012.4  837.59  1316.8     797  1375.3  779.34    1473  769.12
  1648.7  760.89  2097.8  778.31    2282  765.52  2485.3  725.68  2717.4  692.15
    2852  695.06  3093.1   681.3  3112.6  679.38    3132   682.3  3200.1  691.58
  3258.4  709.12  3394.5  780.13    3588  859.58  3655.7  902.11  3762.1  936.31
  3839.5  972.39  3994.9 1027.33  4082.5 1049.75  4179.8  1065.2  4364.6 1062.38
#Mann= 3 , 0 , 0
       0     .05       0  3093.1    .045       0    3132      .1       0
#XS Ineff= 2 , 0
         2854.05  695.02
Permanent Ineff=
       F       F
Bank Sta=3093.1,3132
XS Rating Curve= 0 ,0
Exp/Cntr=0.3,0.1

Type RM Length L Ch R = 1 ,17897.7 ,2488.3,2476.1,2459
XS GIS Cut Line= 5
     1512300.993      222277.718     1511544.048      222194.385
      1511141.27      222083.274     1510807.937      222034.663
     1509259.326      222298.552
#Sta/Elev= 30
       0  881.67     166  947.96   234.3  964.15   302.6  968.71   400.3  961.13
   624.8  894.81   722.5  847.64   761.5   835.2   887.8  748.76  1004.4  693.77
  1111.3  684.69    1266  686.94  1362.2  679.14  1381.5  677.93  1391.1  678.46
  1468.1  689.06  1516.2  723.17  1653.7  764.63  1771.5  792.77  2026.8  805.19
  2203.5  823.84  2340.9  815.18  2429.3  799.14  2517.7  793.64  2547.1  802.77
    2606  830.98  2704.2  857.85  2861.3  872.72  2998.8  896.56  3087.1  919.61
#Mann= 3 , 0 , 0
       0     .05       0  1362.2    .045       0  1391.1      .1       0
Bank Sta=1362.2,1391.1
XS Rating Curve= 0 ,0
Exp/Cntr=0.3,0.1

Type RM Length L Ch R = 1 ,15421.6 ,1653.5,1642.4,1629
XS GIS Cut Line= 5
     1511912.104      220361.052     1510388.232      220736.703
     1509492.399      220965.869     1509061.843      221195.036
     1508777.121       221389.48
#Sta/Elev= 30
       0 1051.97    98.1 1038.84   274.7  997.78   333.5  975.89   392.4  972.36
   608.2  923.45   794.6  851.54   961.3  752.69  1039.8  788.88  1098.6  808.37
  1137.9  808.11  1216.4  822.47  1294.8  814.98    1491  858.65  1618.7  867.54
  1756.4  865.64    1904   845.9  1992.5  818.88  2199.1  773.92    2386  720.66
  2513.7  694.39  2757.6   678.3  2767.3   677.5  2786.8  678.09  2855.1  695.27
  2972.2  781.44  3096.8  860.01  3221.4  929.36  3250.1  933.32  3326.7  913.07
#Mann= 3 , 0 , 0
       0      .1       0  2757.6    .045       0  2786.8      .1       0
Bank Sta=2757.6,2786.8
XS Rating Curve= 0 ,0
Exp/Cntr=0.3,0.1

Type RM Length L Ch R = 1 ,13779.2 ,4083.2,4066.7,4044.6
XS GIS Cut Line= 6
     1510370.437      218203.066     1510155.335      218504.173
      1509641.27      219201.329     1509268.007      219730.843
     1508790.576      220520.774      1508666.79      221364.446
#Sta/Elev= 30
       0 1054.63    68.2 1019.64     224  973.99   399.2  900.18     516  923.78
   759.4   947.5   876.1  965.39   924.8  966.14   983.2  954.83  1236.2  888.34
  1334.4  851.83  1481.6  756.03  1511.1  731.73  1560.2  682.63  1579.8  673.28
  1589.6     673  1619.1  673.21  1756.5  684.07  2031.4  684.64  2188.5  700.78
  2286.7   716.1  2483.1  763.72  2767.8  858.96  2905.1  880.73  3061.9  892.76
  3110.9  888.17  3248.2  887.69  3434.4  874.19  3542.2  879.91  3659.8  867.04
#Mann= 3 , 0 , 0
       0      .1       0  1579.8    .045       0  1619.1    .055       0
#XS Ineff= 2 , 0
                         1919.15          686.62
Permanent Ineff=
       F       F
Bank Sta=1579.8,1619.1
XS Rating Curve= 0 ,0
Exp/Cntr=0.3,0.1

Type RM Length L Ch R = 1 ,9712.5  ,2344,2353,2358
XS GIS Cut Line= 6
     1506802.729      218402.718     1507175.993      219539.871
     1507340.923      220138.829     1507531.895      220867.996
     1507627.382      221380.149     1507827.034      222560.704
#Sta/Elev= 30
       0  890.79    98.1  877.01     206  849.03   353.2  795.44   510.1  747.78
     569  748.63   676.9  770.52   794.6  771.34   971.2  732.52  1030.1  727.96
  1293.9  760.93  1400.7  747.02  1517.2  720.91  1808.4  723.78  2033.5  691.82
  2131.4  685.86  2493.6  701.03  2748.8  669.85  2758.2   669.8  2788.1  669.88
  2935.6  680.12  2994.5  694.99  3063.4  732.16  3181.2  821.28  3387.3  932.82
  3544.3  957.15  3779.8  976.11  4133.1 1042.35  4182.2 1044.38  4290.2 1033.11
#Mann= 3 , 0 , 0
       0      .1       0  2748.8    .045       0  2788.1     .06       0
Bank Sta=2748.8,2788.1
XS Rating Curve= 0 ,0
Exp/Cntr=0.3,0.1

Type RM Length L Ch R = 1 ,7359.5  ,1316.4,1329.8,1342.8
XS GIS Cut Line= 4
     1506624.772      218382.276     1506555.327      219229.498
     1506485.883      219666.998     1506173.383      221423.942
#Sta/Elev= 30
       0  863.32   107.5  847.78   361.5  831.03   459.2  815.78   556.9  794.46
   625.3  793.02   664.4  787.22   742.6  783.54   898.2  790.62   917.5  780.44
   994.5  718.93    1033  691.58  1081.2  664.37  1100.4  663.05  1119.7  663.14
  1177.5  670.97  1312.6  673.52  1440.1  689.96  1783.3  761.87  2057.8  868.62
  2116.7  879.31  2263.7  884.65  2420.6  911.89  2479.4  917.13  2587.3  946.53
  2665.8  974.25  2763.8  993.18  2871.6 1039.45  2959.9 1072.78  3077.6 1098.87
#Mann= 3 , 0 , 0
       0      .1       0  1081.2    .045       0  1119.7     .05       0
Bank Sta=1081.2,1119.7
XS Rating Curve= 0 ,0
Exp/Cntr=0.3,0.1

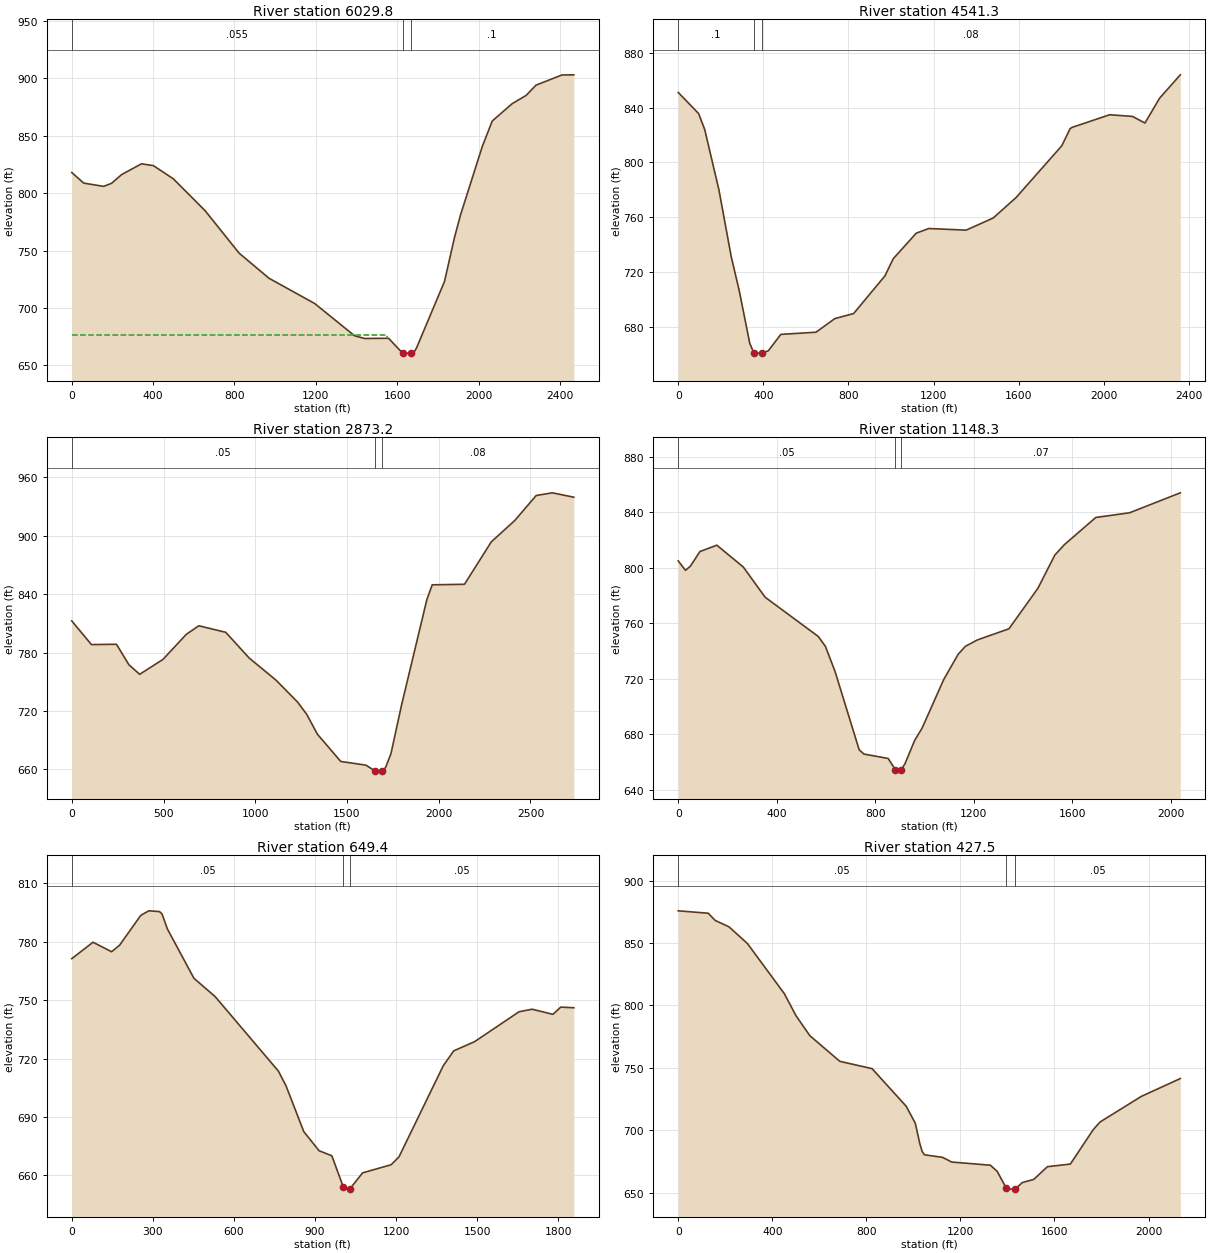
Type RM Length L Ch R = 1 ,6029.8  ,1503.2,1488.4,1473.4
XS GIS Cut Line= 4
     1506215.049      218132.276     1505395.605      219243.387
     1505096.994      219569.776     1505103.938      220215.609
#Sta/Elev= 30
       0  818.04    58.8  808.79   156.7  805.96   195.8  808.63   244.8  816.17
   342.7  825.62   401.4  824.03   499.4  812.53     656   784.7   822.5  747.82
   969.4  725.91  1194.6  703.83  1390.4  675.73  1439.6  673.36  1557.6  673.55
  1626.4  660.71  1636.2   660.6  1665.7  660.61  1685.4  662.07  1695.2  665.11
  1832.8  723.04  1881.7  761.24    1911  780.72  2018.7  840.78  2067.6  862.92
  2165.5  878.02    2234  885.21  2282.9   894.2  2410.1  903.05  2468.8  903.18
#Mann= 3 , 0 , 0
       0    .055       0  1626.4    .045       0  1665.7      .1       0
#XS Ineff= 2 , 0
         1550.58  676.53
Permanent Ineff=
       F       F
Bank Sta=1626.4,1665.7
XS Rating Curve= 0 ,0
Exp/Cntr=0.3,0.1

Type RM Length L Ch R = 1 ,4541.3  ,1657.4,1668.1,1675.1
XS GIS Cut Line= 5
     1504721.994      217757.276     1504645.605       218014.22
     1504610.883      218382.276     1504680.327      218868.387
     1504916.438       220076.72
#Sta/Elev= 30
       0  851.14    95.7   835.7   124.5  824.02   191.5  779.77   248.9  731.25
   287.5  705.73   336.2  667.78   355.6  660.68   365.4   660.6   394.5   660.6
   423.7  662.34   482.1   674.3   647.6  675.89     736  685.83   824.4  689.52
   971.7  717.07  1010.9  729.64    1119  748.28  1177.6  751.67  1353.5   750.5
  1480.6  759.37    1588   774.3    1803  812.16  1842.1  824.68  1851.9  825.62
  2027.8  834.82  2135.2  833.61  2193.9  828.77  2262.3  846.85    2360     864
#Mann= 3 , 0 , 0
       0      .1       0   355.6    .045       0   394.5     .08       0
Bank Sta=355.6,394.5
XS Rating Curve= 0 ,0
Exp/Cntr=0.3,0.1

Type RM Length L Ch R = 1 ,2873.2  ,1701.8,1724.9,1745.8
XS GIS Cut Line= 5
     1504388.661      217736.442     1504034.494       218201.72
     1503749.772      218868.387     1503513.661      219340.609
     1503194.216      220180.887
#Sta/Elev= 30
       0  812.53   107.2   788.2   243.6  788.52   311.9  767.35   370.3  757.66
     497  772.94   623.9  798.66   692.5  807.54   839.4  800.81   966.8  774.41
  1113.7  751.56  1231.3     729  1280.3  716.57    1339  696.04  1466.1  668.05
    1603  664.26  1651.9   658.5  1671.4   658.1    1691   658.1  1710.5  661.84
  1739.8  676.07  1798.5  726.85  1935.3  834.28  1964.6  849.63  2140.5  850.19
  2287.1  893.92  2414.1  915.63  2531.4  941.45  2619.3  944.21  2736.6  939.71
#Mann= 3 , 0 , 0
       0     .05       0  1651.9    .045       0    1691     .08       0
Bank Sta=1651.9,1691
XS Rating Curve= 0 ,0
Exp/Cntr=0.3,0.1

Type RM Length L Ch R = 1 ,1148.3  ,498.9,498.9,497.7
XS GIS Cut Line= 4
     1504367.827      217618.387     1503603.938      217590.609
     1503263.661       217639.22     1502784.494      218437.831
#Sta/Elev= 30
       0  805.03    29.4  798.27      49  801.17    88.2  811.81   156.8  816.38
   264.6  800.58   352.8  778.86   568.4  750.57   597.8   743.4     637  725.28
     735  668.72   754.6  665.64   852.8  662.47   882.2  654.32   892.1  653.33
  904.79654.0171   921.5  658.83   960.8  675.62   990.3  684.26  1078.7  719.53
  1137.5  737.78    1167  743.46    1216  748.08  1343.4  756.04    1461  785.26
  1529.7  809.22  1568.9  816.83  1696.3  836.39  1833.6  839.77  2039.5  854.17
#Mann= 3 , 0 , 0
       0     .05       0   882.2    .045       0  904.79     .07       0
Bank Sta=882.2,904.79
XS Rating Curve= 0 ,0
Exp/Cntr=0.3,0.1

Type RM Length L Ch R = 1 ,649.4   ,226.2,221.9,217.9
XS GIS Cut Line= 6
      1504563.14      217308.491     1503860.015      217167.866
     1503646.473      217131.408     1503487.619      217157.449
     1503234.147      217275.215     1502917.306      217639.799
#Sta/Elev= 30
       0  771.23    78.6  779.68   147.3  774.79   176.8  778.13   255.4  793.47
   284.9  795.78   324.2   795.4     334  794.16   353.6  786.52   451.8   761.2
   530.4  751.77   764.1   713.6   792.4  706.06   858.3   682.5   914.8   672.7
   962.1   670.1  1004.6  654.02  1009.4     653  1028.4  653.07  1075.7  661.33
  1181.4  665.52  1210.3  669.52  1374.2   716.3  1412.8  723.93  1490.1  728.66
  1654.3  743.98  1702.6  745.31  1779.9  742.68  1808.9  746.38  1857.2  746.05
#Mann= 3 , 0 , 0
       0     .05       0  1004.6    .045       0  1028.4     .05       0
Bank Sta=1004.6,1028.4
XS Rating Curve= 0 ,0
Exp/Cntr=0.3,0.1

Type RM Length L Ch R = 1 ,427.5   ,120.2,123.7,125.8
XS GIS Cut Line= 6
     1504933.799      216776.373     1504100.466      216814.567
     1503805.327      216865.493     1503577.897      216914.104
     1503423.383      216971.396     1502945.952      217341.188
#Sta/Elev= 30
       0  875.73   127.6  873.81     157  868.06   215.9  862.92   294.4  849.53
   451.4  809.37   500.5   791.9   559.4  775.84     687  755.29   824.4  749.42
   969.5  719.29  1008.1  705.74  1027.4  689.32  1037.1  683.26  1046.8  680.49
    1124  678.44  1162.8  674.68  1327.5  672.14  1356.6  667.14  1395.4  653.64
  1414.7     653  1434.1  653.19  1463.2  658.26  1511.7  660.77    1570  670.97
  1667.4  673.06  1764.8  700.62    1794  706.76  1969.4  727.23    2135   741.5
#Mann= 3 , 0 , 0
       0     .05       0  1395.4    .045       0  1434.1     .05       0
Bank Sta=1395.4,1434.1
XS Rating Curve= 0 ,0
Exp/Cntr=0.3,0.1

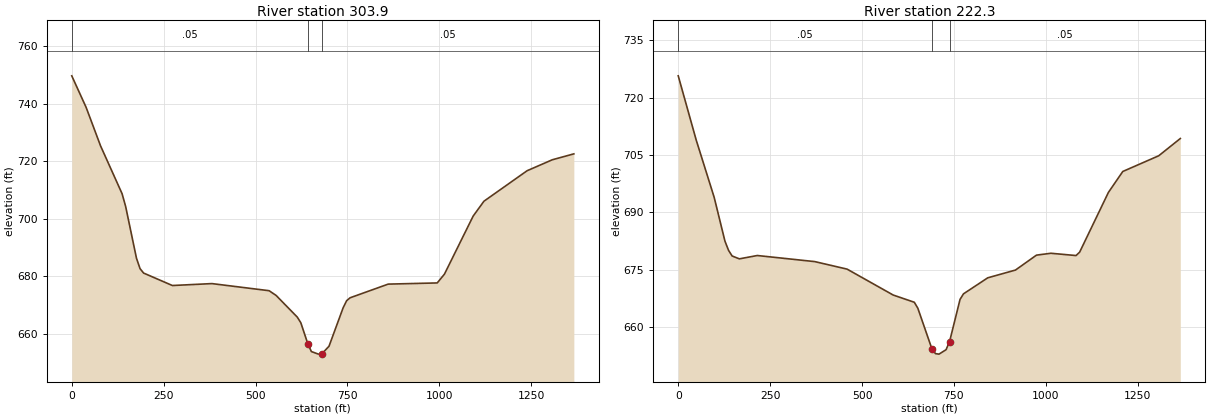
Type RM Length L Ch R = 1 ,303.9   ,81.7,81.6,80.9
XS GIS Cut Line= 5
     1504096.994      216733.549     1503612.619      216799.521
     1503362.619      216867.229     1503178.591      216962.715
     1502860.883      217223.132
#Sta/Elev= 30
       0  749.79    39.1  738.81    78.2  725.47   136.9  708.79   146.6  704.35
     176  686.38   185.8  682.72   195.5  681.19   273.8  676.86   381.3  677.53
   536.8  675.06     556  673.41   613.6  665.87   623.2  663.91   642.3  656.56
   651.9  653.89   671.1     653   680.7  653.15   699.9  655.75   738.3  669.11
   747.8  671.57   757.3   672.6   860.9  677.35   994.3  677.76  1013.9  680.81
  1092.1  701.01  1121.4  706.18  1238.8  716.78  1307.3  720.59    1366  722.65
#Mann= 3 , 0 , 0
       0     .05       0   642.3    .045       0   680.7     .05       0
Bank Sta=642.3,680.7
XS Rating Curve= 0 ,0
Exp/Cntr=0.3,0.1

Type RM Length L Ch R = 1 ,222.3   ,202.6,222.3,242
XS GIS Cut Line= 5
     1504088.313      216660.632     1503603.938      216726.604
     1503353.938      216794.313     1503169.911      216889.799
     1502852.202      217150.215
#Sta/Elev= 30
       0  725.72    48.9  708.93    97.8  693.95   127.1   682.5   136.9  680.09
   146.6  678.62   166.2  677.87   215.1  678.74   371.5  677.15   459.5  675.18
   584.8  668.41   642.3  666.52   651.9  664.96   690.3   654.3   699.9  653.09
   709.5  652.96   728.7  654.12   738.3  656.26   766.7  667.26   776.1  668.72
   842.1  672.91   917.5  674.94   974.7  678.84  1013.9  679.33  1082.3  678.73
  1092.1  679.62  1170.4  695.24  1209.5  700.71  1307.3  704.82    1366  709.33
#Mann= 3 , 0 , 0
       0     .05       0   690.3    .045       0   738.3     .05       0
Bank Sta=690.3,738.3
XS Rating Curve= 0 ,0
Exp/Cntr=0.3,0.1

Chan Stop Cuts=-1
Use User Specified Reach Order=0
Composite Channel Slope=5